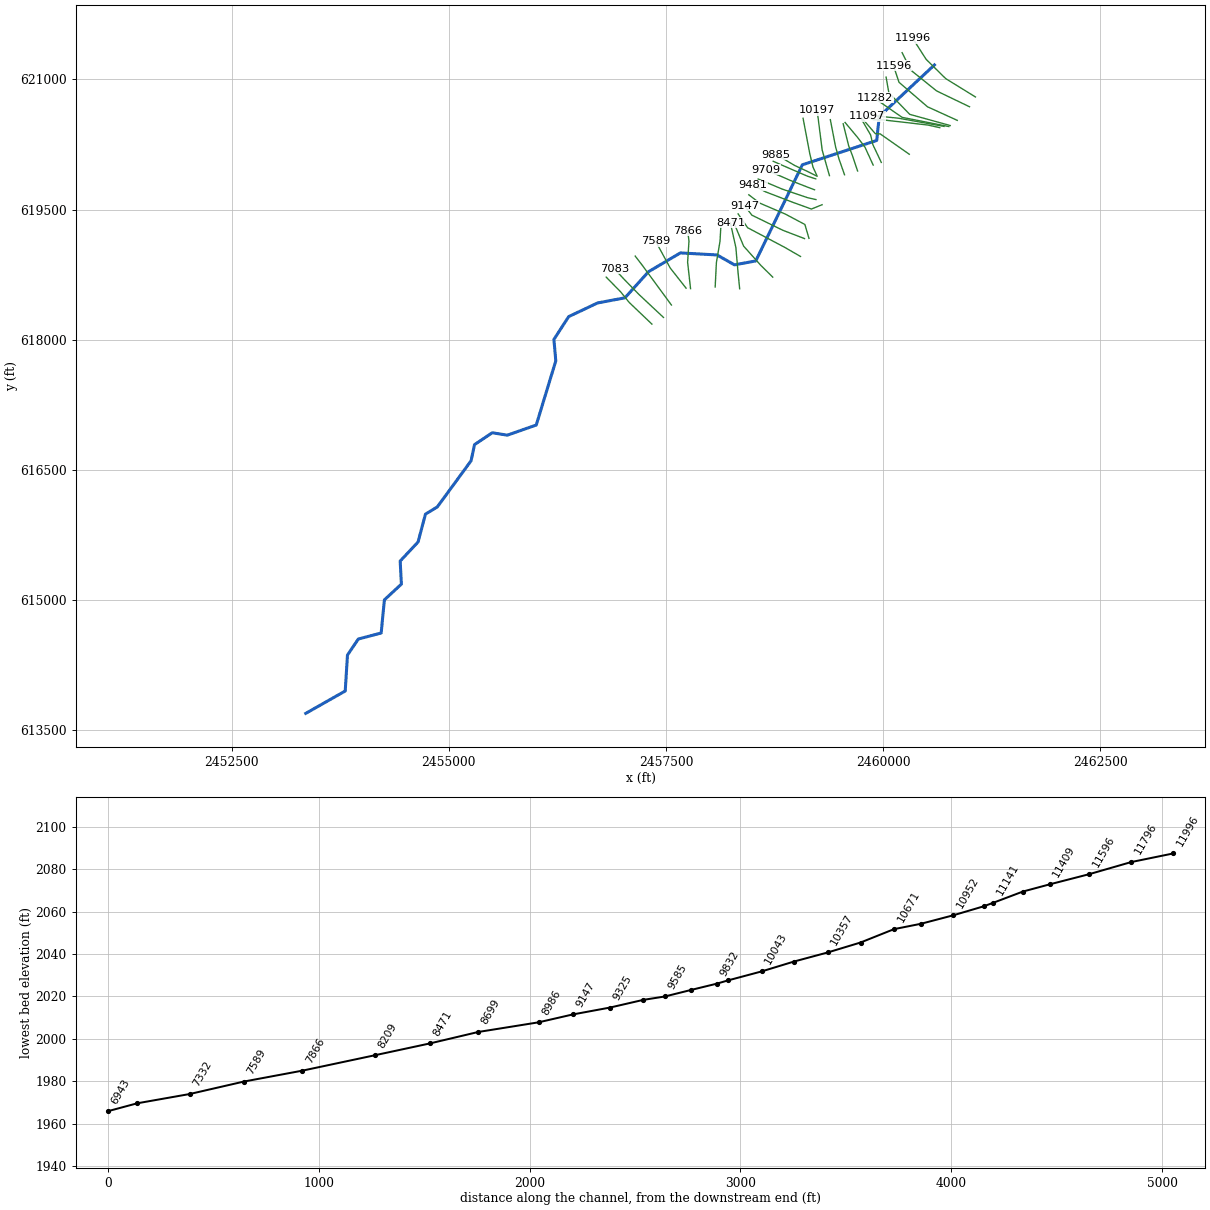
--- DRYRN1.prj (project) ---

Proj Title=DRYRN1
Current Plan=p01
Default Exp/Contr=0,0
English Units
Geom File=g01
Flow File=f01
Flow File=f02
Plan File=p01
Background Map Layer=QC
BEGIN DESCRIPTION:
Stream Name:Dry Run 1
Flood Zone: Zone A
Pendleton County, WV
WVDHSEM Flood Warning & Analysis Mapping
HEC-RAS Version: 5.0.7
Hydrology Method:
Regression
Model Notes:
Tie in with Trout Run at the downstream end.
END DESCRIPTION:
DSS Export Rating Curves= 0
DSS Export Rating Curve Sorted= 0
DSS Export Volume Flow Curves= 0
DXF OffsetX= 0
DXF OffsetY= 0
DXF ScaleX= 0
DXF ScaleY= 0

--- DRYRN1.p01 (plan) ---

Plan Title=Floodplain
Program Version=5.07
Short Identifier=Floodplain
Geom File=g01
Flow File=f01
Subcritical Flow
K Sum by GR= 0
Std Step Tol= 0.01
Critical Tol= 0.01
Num of Std Step Trials= 20
Max Error Tol= 0.3
Flow Tol Ratio= 0.001
Split Flow NTrial= 30
Split Flow Tol= 0.02
Split Flow Ratio= 0.02
Log Output Level= 0
Friction Slope Method= 1
Unsteady Friction Slope Method= 2
Unsteady Bridges Friction Slope Method= 1
Parabolic Critical Depth
Global Vel Dist= 0 , 0 , 0
Global Log Level= 0
CheckData=True
Encroach Param=-1 ,0,0, 0
Mapping Interval=1HOUR
Computation Time Step Use Courant=        0
Computation Time Step Use Time Series=    0
Computation Time Step Count To Double=0
Computation Time Step Max Doubling=0
Computation Time Step Max Halving=0
Computation Time Step Residence Courant=0
Run HTab= 0
Run UNet= 0
Run Sediment= 0
Run PostProcess= 0
Run WQNet= 0
Run RASMapper= 0
UNET Theta= 0
UNET Theta Warmup= 0
UNET ZTol= 0
UNET ZSATol= 0
UNET MxIter= 0
UNET Max Iter WO Improvement= 0
UNET MaxInSteps= 0
UNET DtIC= 0
UNET DtMin= 0
UNET MaxCRTS= 0
UNET WFStab= 0
UNET SFStab= 0
UNET WFX= 1
UNET SFX= 1
UNET 1D Methodology=Finite Difference
UNET DSS MLevel= 1
UNET Pardiso=0
UNET DZMax Abort= 0
UNET Use Existing IB Tables= 0
UNET Froude Reduction=False
UNET Froude Limit= 0
UNET Froude Power= 0
UNET D1 Cores= 0
UNET D2 Coriolis=0
UNET D2 Cores= 0
UNET D2 Theta= 1
UNET D2 Theta Warmup= 1
UNET D2 Z Tol= 0.01
UNET D2 Volume Tol= 0.01
UNET D2 Max Iterations= 20
UNET D2 Equation= 0
UNET D2 RampUpFraction=0.1
UNET D2 TimeSlices= 1
UNET D2 BCVolumeCheck=0
UNET D1D2 MaxIter= 0
UNET D1D2 ZTol=0.01
UNET D1D2 QTol=0.1
UNET D1D2 MinQTol=1
Write IC File= 0
Write IC File at Fixed DateTime=0
Write IC File at Sim End=0
Echo Input=False
Echo Parameters=False
Echo Output=False
Write Detailed= 0
HDF Write Warmup=0
HDF Write Time Slices=0
HDF Flush=0
HDF Face Node Velocities=0
HDF Compression= 1
HDF Chunk Size= 1
HDF Spatial Parts= 1
HDF Use Max Rows=0
HDF Fixed Rows= 1
Calibration Method= 0
Calibration Iterations= 20
Calibration Max Change=0.05
Calibration Tolerance=0.2
Calibration Maximum=1.5
Calibration Minimum=0.5
Calibration Optimization Method= 1
WQ AD Non Conservative
WQ ULTIMATE=-1
WQ Max Comp Step=1HOUR
WQ Output Interval=15MIN
WQ Output Selected Increments= 0
WQ Output face flow=0
WQ Output face velocity=0
WQ Output face area=0
WQ Output face dispersion=0
WQ Output cell volume=0
WQ Output cell surface area=0
WQ Output cell continuity=0
WQ Output cumulative cell continuity=0
WQ Output face conc=0
WQ Output face dconc_dx=0
WQ Output face courant=0
WQ Output face peclet=0
WQ Output face adv mass=0
WQ Output face disp mass=0
WQ Output cell mass=0
WQ Output cell source sink temp=0
WQ Output nsm pathways=0
WQ Output nsm derived pathways=0
WQ Output MaxMinRange=-1
WQ Daily Max Min Mean=-1
WQ Daily Range=0
WQ Daily Time=0
WQ Create Restart=0
WQ Fixed Restart=0
WQ System Summary=0
WQ Write To DSS=0
WQ Use Fixed Temperature=0
Sorting and Armoring Iterations= 10
XS Update Threshold= 0.02
Bed Roughness Predictor= 0
Hydraulics Update Threshold= 0.02
Energy Slope Method= 1
Volume Change Method= 1
Sediment Retention Method= 0
XS Weighting Method= 0
Number of US Weighted Cross Sections= 1
Number of DS Weighted Cross Sections= 1
Upstream XS Weight=0
Main XS Weight=1
Downstream XS Weight=0
Number of DS XS's Weighted with US Boundary= 1
Upstream Boundary Weight= 1
Weight of XSs Associated with US Boundary= 0
Number of US XS's Weighted with DS Boundary= 1
Downstream Boundary Weight= 0.5
Weight of XSs Associated with DS Boundary= 0.5
Percentile Method= 0
Sediment Output Level= 3
Mass or Volume Output= 0
Output Increment Type= 1
Profile and TS Output Increment= 1
XS Output Flag= 0
XS Output Increment= 10
Write Gradation File= 0
Read Gradation Hotstart= 0
Write HDF5 File= 1
Write Binary Output= 1
Write DSS Sediment File= 0
SV Curve= 0
Specific Gage Flag= 0

--- DRYRN1.f01 (steady flow) ---

Flow Title=Flows
Program Version=5.07
Number of Profiles= 6
Profile Names=P100yr,P10yr,P25yr,P50yr,P500yr,P101yr
River Rch & RM=DRYRN1,Main            ,11996
     530     248     350     437     776     644
River Rch & RM=DRYRN1,Main            ,10799
     607     284     401     501     891     739
River Rch & RM=DRYRN1,Main            ,10043
    1017     472     669     838    1500    1238
River Rch & RM=DRYRN1,Main            ,8986
    1151     533     756     948    1699    1401
River Rch & RM=DRYRN1,Main            ,5704
    1300     601     854    1070    1921    1582
Boundary for River Rch & Prof#=DRYRN1,Main            , 1
Up Type= 0
Dn Type= 3
Dn Slope=0.03231
Boundary for River Rch & Prof#=DRYRN1,Main            , 2
Up Type= 0
Dn Type= 3
Dn Slope=0.03231
Boundary for River Rch & Prof#=DRYRN1,Main            , 3
Up Type= 0
Dn Type= 3
Dn Slope=0.03231
Boundary for River Rch & Prof#=DRYRN1,Main            , 4
Up Type= 0
Dn Type= 3
Dn Slope=0.03231
Boundary for River Rch & Prof#=DRYRN1,Main            , 5
Up Type= 0
Dn Type= 3
Dn Slope=0.03231
Boundary for River Rch & Prof#=DRYRN1,Main            , 6
Up Type= 0
Dn Type= 3
Dn Slope=0.03231
DSS Import GetInterval= 0
DSS Import GetPeak= 0
DSS Import FillOption= 0

--- DRYRN1.f02 (steady flow) ---

Flow Title=Flows_Trial
Program Version=5.07
Number of Profiles= 6
Profile Names=P100yr,P10yr,P25yr,P50yr,P500yr,P101yr
River Rch & RM=DRYRN1,Main            ,11996
     530     248     350     437     776     644
River Rch & RM=DRYRN1,Main            ,10671
     607     284     401     501     891     739
River Rch & RM=DRYRN1,Main            ,10043
    1017     472     669     838    1500    1238
River Rch & RM=DRYRN1,Main            ,8986
    1151     533     756     948    1699    1401
River Rch & RM=DRYRN1,Main            ,5704
    1300     601     854    1070    1921    1582
Boundary for River Rch & Prof#=DRYRN1,Main            , 1
Up Type= 0
Dn Type= 3
Dn Slope=0.03231
Boundary for River Rch & Prof#=DRYRN1,Main            , 2
Up Type= 0
Dn Type= 3
Dn Slope=0.03231
Boundary for River Rch & Prof#=DRYRN1,Main            , 3
Up Type= 0
Dn Type= 3
Dn Slope=0.03231
Boundary for River Rch & Prof#=DRYRN1,Main            , 4
Up Type= 0
Dn Type= 3
Dn Slope=0.03231
Boundary for River Rch & Prof#=DRYRN1,Main            , 5
Up Type= 0
Dn Type= 3
Dn Slope=0.03231
Boundary for River Rch & Prof#=DRYRN1,Main            , 6
Up Type= 0
Dn Type= 3
Dn Slope=0.03231
DSS Import GetInterval= 0
DSS Import GetPeak= 0
DSS Import FillOption= 0

--- DRYRN1.g01 (geometry) ---

Geom Title=Geometry
Program Version=5.07

River Reach=DRYRN1          ,Main
Reach XY= 30
     2460589.194      621165.204     2459953.958      620571.127
     2459925.022      620295.452     2459068.628      620014.723
     2458532.831      618907.589     2458287.658      618862.334
     2458086.798      618976.514     2457664.703      618999.979
     2457297.302      618782.956     2457027.055      618482.784
     2456711.726      618423.591     2456379.135      618266.224
     2456209.346      618003.707     2456230.842      617756.179
     2456006.002      617017.589     2455673.013      616900.944
     2455499.376      616928.543     2455295.223      616791.898
     2455255.972       616606.22     2454866.814      616074.128
     2454730.657      615991.261     2454645.484      615670.173
     2454439.643      615450.519     2454453.619      615185.296
     2454258.036      615003.869     2454220.836      614622.155
     2453957.972      614552.971     2453833.128      614368.605
     2453807.142      613954.234     2453352.815      613696.534

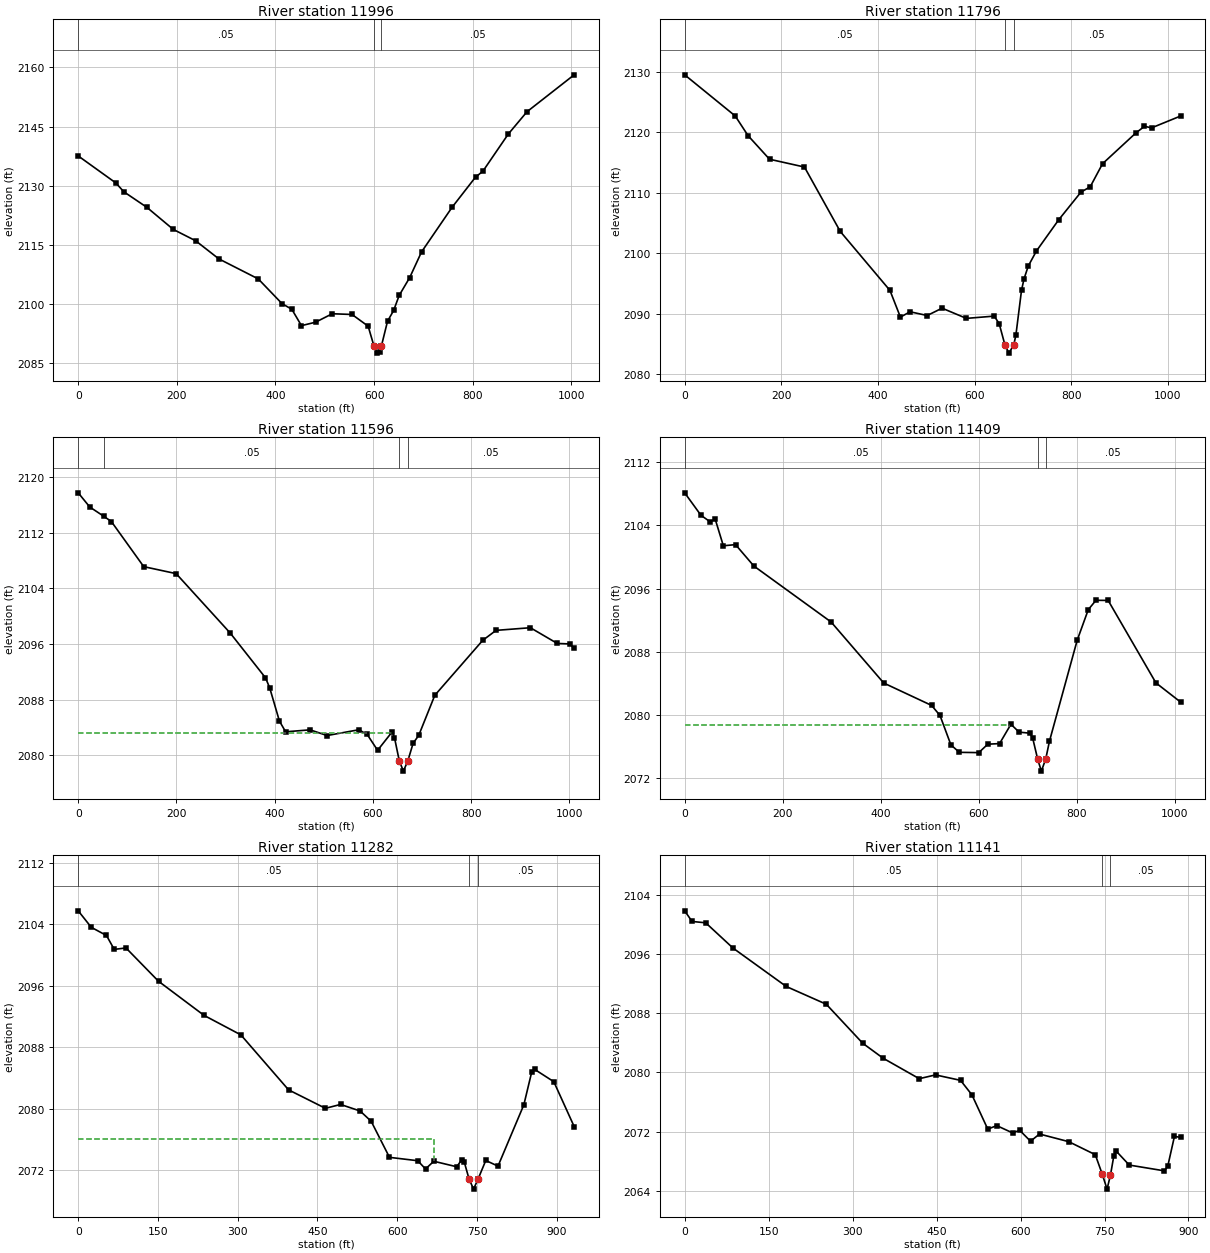
Type RM Length L Ch R = 1 ,11996   ,199.6,200.4,201.8
XS GIS Cut Line= 4
 2461061.3539299620796.1831038252460718.68748392621007.830026344
2460493.60266156621229.5553737452460339.06681337 621471.43757091
#Sta/Elev= 30
       02137.56376.522092130.689 92.39432128.481 139.4092124.505192.77662118.922
238.13982116.041285.15452111.451365.07952106.366413.36812100.084433.16772098.662
452.71952094.507481.28522095.378515.19432097.525555.3171 2097.34587.96642094.369
  599.812089.322 606.6162087.535611.36362087.927  614.822089.323  627.27 2095.62
639.64872098.357650.96272102.189672.18842106.691696.21882113.204758.26842124.548
805.73832132.188820.60242133.676872.1885 2143.12910.16192148.7811005.744 2158.14
#Mann= 3 ,-1 , 0
       0     .05       0  599.81    .045       0  614.82     .05       0
Bank Sta=599.81,614.82
XS Rating Curve= 0 ,0
Exp/Cntr(USF)=0,0
Exp/Cntr=0.3,0.1

Type RM Length L Ch R = 1 ,11796   ,199.4,199.3,198.9
XS GIS Cut Line= 4
2460992.95817761620683.3318225172460614.06453104 620865.83556851
2460318.48781198 621103.883932852460217.31725714621306.225042538
#Sta/Elev= 30
       02129.489104.57282122.685131.2119 2119.42175.61032115.524247.85622114.233
321.95312103.577 424.8192093.819446.42672089.402466.3404 2090.29501.8581 2089.67
532.67382090.883582.97782089.195640.52862089.572650.80052088.334   662.72084.812
670.94732083.447  680.992084.811685.39122086.412697.02392093.827702.15992095.704
710.99462097.852727.83962100.336774.06312105.512820.01122110.082 839.2122110.965
864.73252114.781933.12692119.831951.55052120.975966.10092120.7111026.2972122.675
#Mann= 3 ,-1 , 0
       0     .05       0   662.7    .045       0  680.99     .05       0
Bank Sta=662.7,680.99
XS Rating Curve= 0 ,0
Exp/Cntr(USF)=0,0
Exp/Cntr=0.3,0.1

Type RM Length L Ch R = 1 ,11596   ,187.8,187.4,186
XS GIS Cut Line= 4
2460852.11289538620526.6166493272460508.92650345620683.331822517
2460181.61000249620965.0223869852460118.13043866621155.461078457
#Sta/Elev= 30
       0 2117.7123.490332115.676   51.63 2114.3667.46354 2113.59133.42332107.105
199.38322106.102309.31622097.581381.34572091.135389.85482089.708409.70922084.919
422.37192083.375 472.1092083.659506.80932082.842571.38142083.669588.3995    2083
609.61962080.719639.45392083.386644.02012082.532  653.752079.214662.14472077.727
  671.242079.214681.99922081.736693.34462082.856726.12982088.622823.73372096.518
850.80442097.949920.7102 2098.33 975.5232096.0691000.8212096.0031009.8552095.363
#Mann= 4 ,-1 , 0
       0      .1       0   51.63     .05       0  653.75    .045       0
  671.24     .05       0
#XS Ineff= 2 , 0
          640.36 2083.25
Permanent Ineff=
       F       F
Bank Sta=653.75,671.24
XS Rating Curve= 0 ,0
Exp/Cntr(USF)=0,0
Exp/Cntr=0.3,0.1

Type RM Length L Ch R = 1 ,11409   ,125,126.6,128.3
XS GIS Cut Line= 4
2460770.77970423620467.1045582422460304.60165739620596.047422259
2460064.56955669620844.0144684462460032.82977477 621024.53447807
#Sta/Elev= 30
       0 2108.1133.237492105.27151.870232104.45162.288832104.78178.889592101.414
103.79072101.561141.14252098.858298.84972091.778406.22742084.063503.9786 2081.23
521.04192079.959543.31022076.243560.55472075.301600.15792075.265 618.6272076.331
642.58992076.406665.7859 2078.85682.48722077.855704.82352077.721710.32262077.068
  720.222074.474727.89832072.925  736.882074.475744.42682076.711801.00272089.469
823.63322093.342839.33122094.523864.20652094.505961.67912084.0831012.0842081.653
#Mann= 3 ,-1 , 0
       0     .05       0  720.22    .045       0  736.88     .05       0
#XS Ineff= 2 , 0
          662.07 2078.79
Permanent Ineff=
       F       F
Bank Sta=720.22,736.88
XS Rating Curve= 0 ,0
Exp/Cntr(USF)=0,0
Exp/Cntr=0.3,0.1

Type RM Length L Ch R = 1 ,11282   ,138.6,141,144.7
XS GIS Cut Line= 4
2460754.91379963620455.5646740942460217.05868602620561.392647836
2459955.60133913620742.5452381832459906.51965803620787.372285421
#Sta/Elev= 30
       02105.77124.632152103.62153.169012102.56167.69878 2100.7589.859252100.938
151.00962096.603236.6202 2092.16 305.9242089.619395.61122082.462 464.9152080.058
493.4519 2080.56530.14212079.711550.9823 2078.37585.40222073.674638.57562073.234
653.17442072.161668.76572073.165711.88482072.447721.30262073.364726.16892073.037
  734.86  2070.9743.50542069.536  752.332070.899766.50232073.267789.49912072.531
838.09362080.513852.74042084.741858.48962085.125894.49542083.521932.72132077.684
#Mann= 3 ,-1 , 0
       0     .05       0  734.86    .045       0  752.33     .05       0
#XS Ineff= 2 , 0
       0  668.77    2076               0
Permanent Ineff=
       F       F
Bank Sta=734.86,752.33
XS Rating Curve= 0 ,0
Exp/Cntr(USF)=0,0
Exp/Cntr=0.5,0.3

Type RM Length L Ch R = 1 ,11141   ,43.4,44.4,45.4
XS GIS Cut Line= 4
2460699.71631626620457.0509823212460179.10454345 620551.05033019
2459921.08356427620577.4453470712459833.45566469620620.392971195
#Sta/Elev= 30
       02101.826  13.1812100.391  37.5692100.208  86.3452096.793 181.4572091.606
 252.9972089.205 318.0322083.938 354.614 2081.91 419.0252079.149 448.102 2079.66
 492.8132078.924 513.1362076.969 541.4542072.337 557.5372072.807 585.6832071.828
 598.5192072.171  617.852070.703 633.9342071.673 686.0642070.642 733.4852068.885
  745.972066.254  754.562064.229  760.62 2066.11 766.6232068.701 770.6442069.387
 794.215 2067.48 856.9932066.698 862.9722067.315 874.929 2071.35 885.9842071.219
#Mann= 3 , 0 , 0
       0     .05       0  745.97    .045       0  760.62     .05       0
#XS Ineff= 2 , 0
             730  2068.9     775          2068.9
Permanent Ineff=
       F       F
Bank Sta=745.97,760.62
XS Rating Curve= 0 ,0
Exp/Cntr(USF)=0,0
Exp/Cntr=0.5,0.3

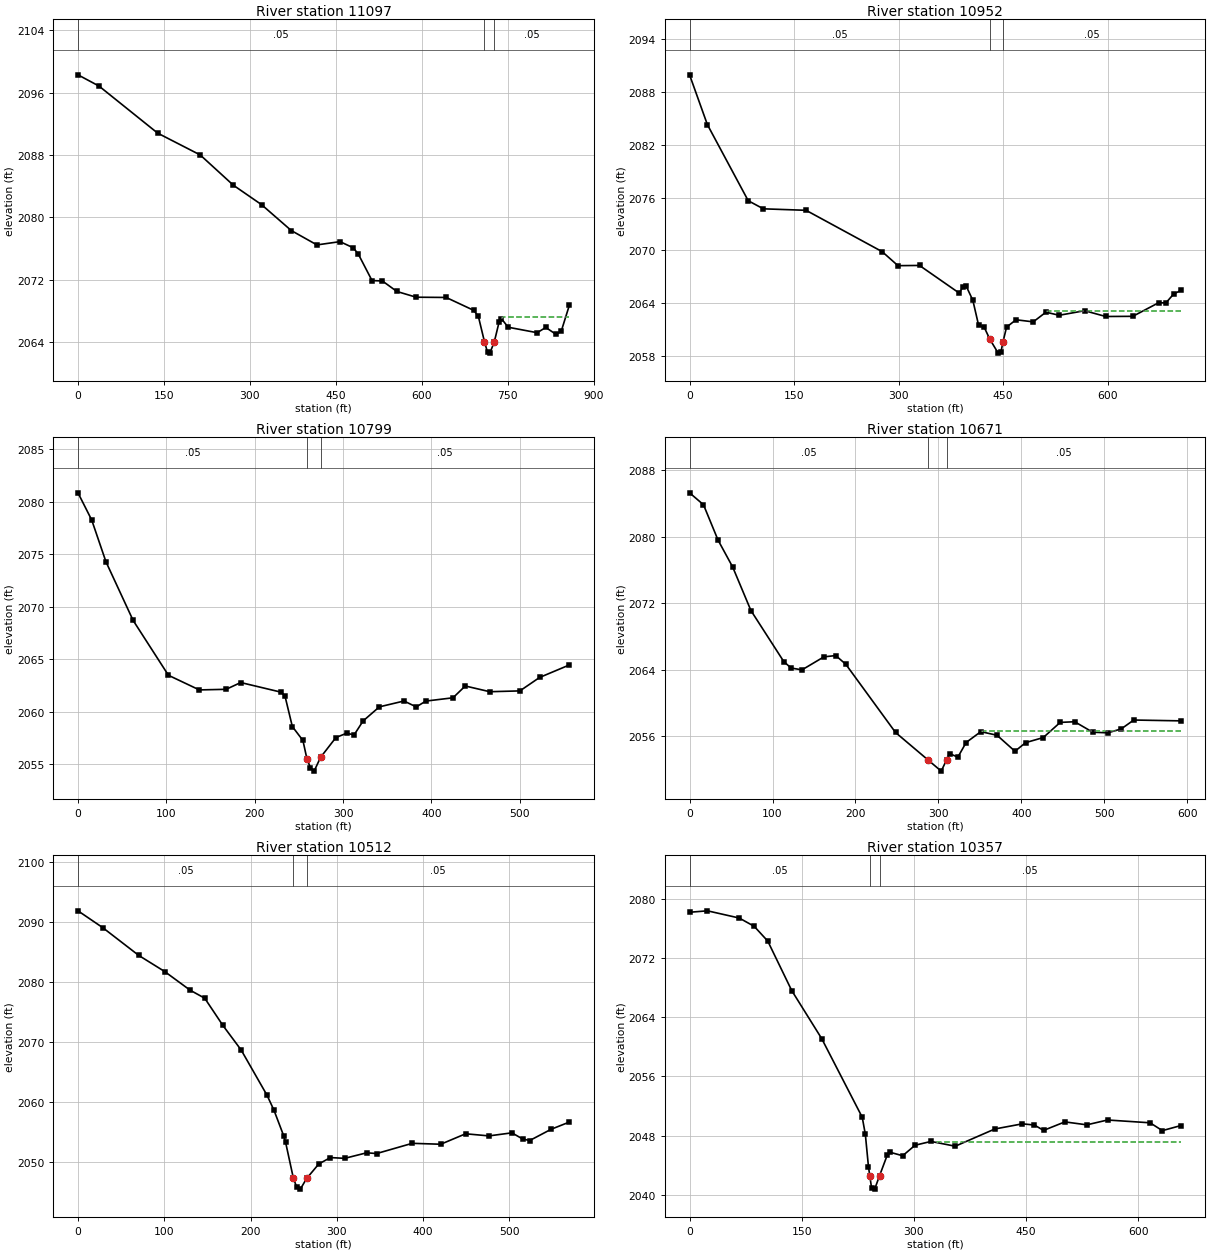
Type RM Length L Ch R = 1 ,11097   ,145.6,145.2,144.3
XS GIS Cut Line= 5
2460650.54742661620442.5895441882460513.16376434620472.958564268
2459983.87512865620533.6966044292459890.03634743620532.435328964
2459810.45429563620574.195657743
#Sta/Elev= 30
       02098.292  36.6672096.851 139.0812090.808 213.2532088.013 271.041 2084.13
  320.292081.634 372.1712078.312  416.922076.469 457.1822076.889 480.5252076.091
 489.392 2075.25 513.0312071.893  531.092071.845 556.3722070.497 590.0492069.759
  642.392069.727 690.5942068.069 698.5952067.289  709.242064.039 714.5962062.681
 718.5972062.584  726.412064.038 734.5982066.533 738.5982067.024   750.62065.906
 801.1932065.205 816.1992065.879 834.2682064.979 843.3032065.422 857.1832068.696
#Mann= 3 , 0 , 0
       0     .05       0  709.24    .045       0  726.41     .05       0
#XS Ineff= 2 , 0
                          739.45         2067.17
Permanent Ineff=
       F       F
Bank Sta=709.24,726.41
XS Rating Curve= 0 ,0
Exp/Cntr(USF)=0,0
Exp/Cntr=0.5,0.3

Type RM Length L Ch R = 1 ,10952   ,165,152.6,137.6
XS GIS Cut Line= 4
2460299.67595482620136.4048473362459965.28147295620370.473931222
2459909.75141138620372.5457255142459752.35012973620555.111727231
#Sta/Elev= 30
       02089.955  25.5492084.296   84.142075.643  105.852074.721 167.1442074.552
 276.3732069.848 298.9732068.259 329.8772068.283  386.862065.141 391.7422065.791
 396.625 2065.97  406.392064.322 414.7172061.462 422.7232061.252 430.7292059.898
 442.7372058.315  446.742058.446 449.6142059.587 454.745 2061.27 468.3492062.107
 493.065 2061.87  511.232062.969 530.2182062.619 566.8052063.138  596.99 2062.48
 635.8462062.499 672.8162064.039 683.3792064.028 694.4332065.035 704.796 2065.44
#Mann= 3 , 0 , 0
       0     .05       0 430.729    .045       0 449.614     .05       0
#XS Ineff= 2 , 0
                          512.16         2063.05
Permanent Ineff=
       F       F
Bank Sta=430.729,449.614
XS Rating Curve= 0 ,0
Exp/Cntr(USF)=0,0
Exp/Cntr=0.3,0.1

Type RM Length L Ch R = 1 ,10799   ,121.4,128.1,130.4
XS GIS Cut Line= 4
2459977.39209831620042.2950744422459881.07782988620246.322419297
 2459854.5177195620358.7558698172459746.71305071 620544.75789301
#Sta/Elev= 30
       02080.835  15.5712078.241  31.6222074.277  62.4212068.682 102.3952063.457
 137.3822062.063 167.7012062.121 184.2322062.766 230.312 2061.84 234.4232061.445
 242.6432058.575 254.6272057.249 259.083 2055.53 263.1932054.624 267.3032054.328
 274.5762055.637 291.9642057.527 304.2942057.943 312.5142057.772 322.7592059.108
 341.146 2060.45 369.0422061.007 382.9122060.445 393.763    2061 424.5212061.313
 438.3912062.438 466.1312061.892  500.232061.969 522.546 2063.25 556.1312064.437
#Mann= 3 , 0 , 0
       0     .05       0 259.083    .045       0 274.576     .05       0
Bank Sta=259.083,274.576
XS Rating Curve= 0 ,0
Exp/Cntr(USF)=0,0
Exp/Cntr=0.3,0.1

Type RM Length L Ch R = 1 ,10671   ,160,158.5,156
XS GIS Cut Line= 4
2459884.09120553620011.6386878062459790.09185766620216.991109303
2459706.21551648620328.3441829322459560.65836261620502.449980262
#Sta/Elev= 30
       02085.26816.774162083.83834.370752079.57151.967352076.34673.963092071.107
113.55542064.969122.35372064.191135.5512 2063.97161.94612065.536176.22242065.689
 188.3412064.641248.25362056.439     2872053.169303.33942051.787  309.962053.171
 313.3552053.906323.37062053.464333.38622055.231351.07582056.537370.6633  2056.1
392.24172054.176405.06812055.215426.31792055.823 446.778 2057.65464.20822057.729
485.95132056.469504.12922056.394520.33512056.867535.41162057.935 592.1882057.834
#Mann= 3 ,-1 , 0
       0     .05       0     287    .045       0  309.96     .05       0
#XS Ineff= 2 , 0
                          352.74         2056.63
Permanent Ineff=
       F       F
Bank Sta=287,309.96
XS Rating Curve= 0 ,0
Exp/Cntr(USF)=0,0
Exp/Cntr=0.3,0.1

Type RM Length L Ch R = 1 ,10512   ,155.9,155.4,154.6
XS GIS Cut Line= 4
2459704.76937267619943.6699285782459645.47747632620120.099473808
2459602.09316192 620232.898691252459538.46283413620487.420002402
#Sta/Elev= 30
       02091.911  28.7172089.10270.468232084.468100.45432081.785129.99312078.666
146.87252077.335167.97172072.783189.11682068.689219.11642061.135227.16592058.629
238.30862054.408240.5447 2053.33  249.68 2047.26253.40172045.851257.68732045.481
  264.97 2047.26279.11562049.688292.54192050.746309.03432050.616334.47392051.539
346.14222051.418387.37332053.123420.35812052.969449.21992054.714476.30872054.362
502.82032054.872515.18962053.857523.43582053.584548.17442055.459569.33532056.665
#Mann= 3 ,-1 , 0
       0     .05       0  249.68    .045       0  264.97     .05       0
Bank Sta=249.68,264.97
XS Rating Curve= 0 ,0
Exp/Cntr(USF)=0,0
Exp/Cntr=0.3,0.1

Type RM Length L Ch R = 1 ,10357   ,160.2,160.2,160.1
XS GIS Cut Line= 4
2459554.37041608619900.285614177 2459492.1862321620076.715159407
2459451.69420533 620219.883396932459390.95616517620535.142748243
#Sta/Elev= 30
       02078.16923.968262078.362 66.38012077.39186.418212076.272104.55082074.279
136.59272067.601176.6509 2061.12230.89762050.495235.05462048.177239.21152043.832
  240.952042.601243.36842040.963247.52532040.797  254.012042.603264.1529 2045.34
268.30982045.766284.93742045.303301.56512046.723322.85492047.236355.20882046.588
408.16512048.915445.11152049.612461.12132049.445 473.3422048.725501.85692049.873
531.16242049.475558.88682050.127615.73722049.751632.21082048.694656.90872049.376
#Mann= 3 ,-1 , 0
       0     .05       0  240.95    .045       0  254.01     .05       0
#XS Ineff= 2 , 0
                          330.41         2047.19
Permanent Ineff=
       F       F
Bank Sta=240.95,254.01
XS Rating Curve= 0 ,0
Exp/Cntr(USF)=0,0
Exp/Cntr=0.3,0.1

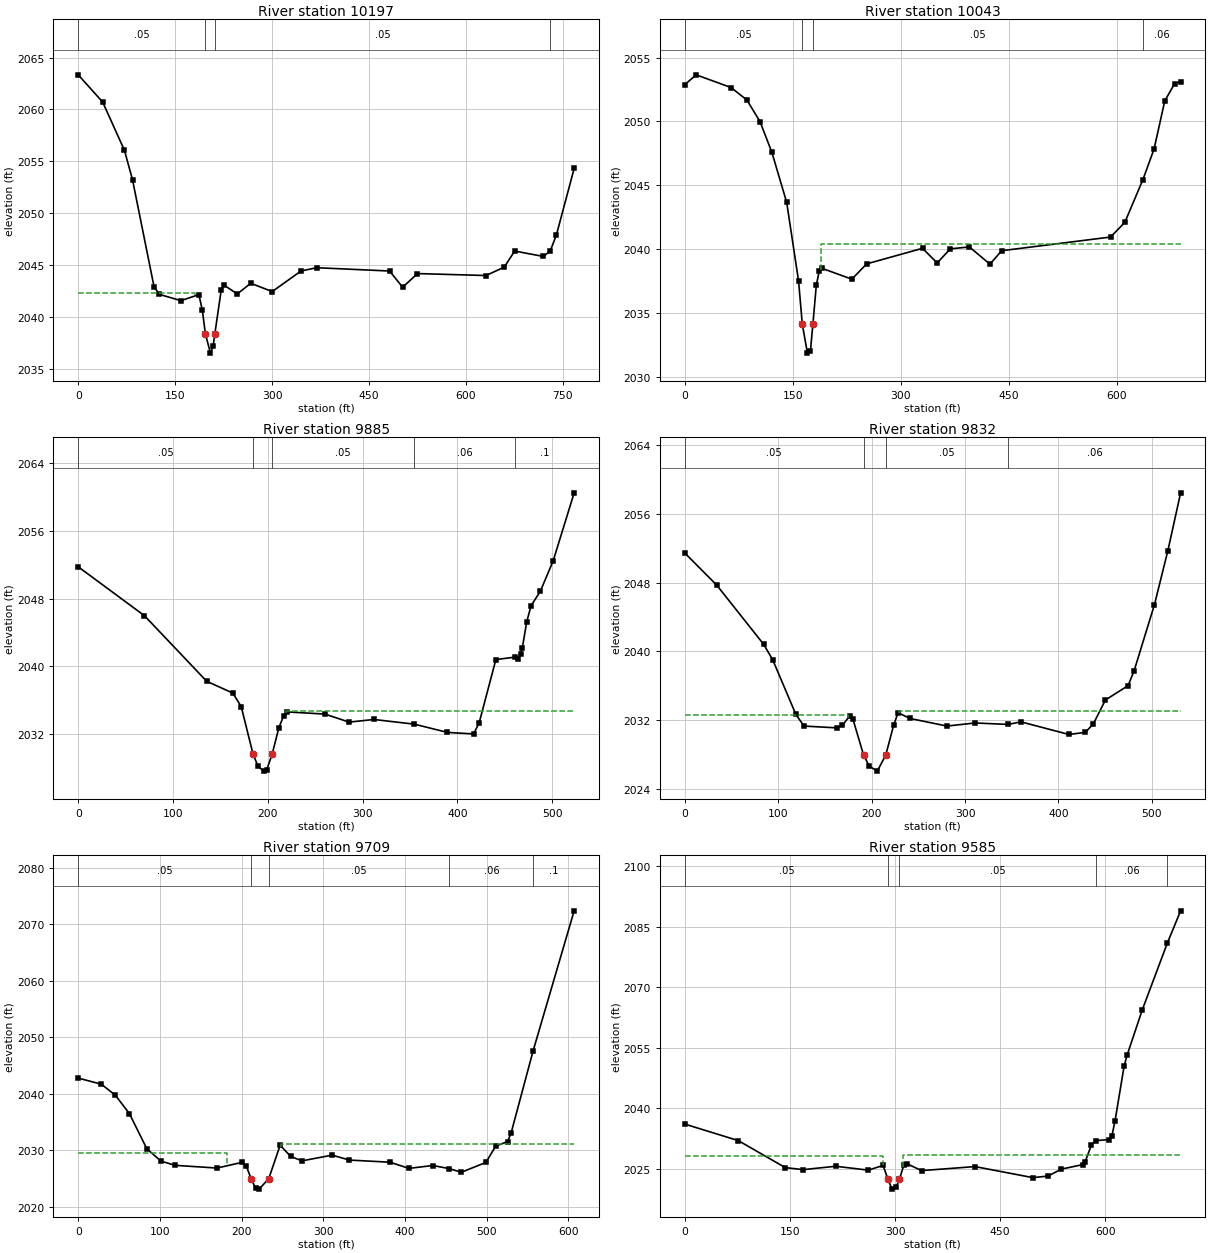
Type RM Length L Ch R = 1 ,10197   ,153.7,153.5,153.2
XS GIS Cut Line= 4
2459380.83315848619890.1626074832459347.57185077620005.854112552
 2459296.9568173620185.1759454092459239.11106477620642.157390432
#Sta/Elev= 30
       0 2063.3437.835192060.71771.512292056.06283.998382053.226117.29462042.912
125.61152042.164158.86172041.563186.71562042.138 192.1122040.616  196.762038.358
204.58092036.499208.73722037.153  211.372038.361 221.2062042.558225.36232043.065
246.14382042.208266.92522043.235300.17552042.437 344.722 2044.42368.91352044.738
481.80722044.418501.96682042.852524.95312044.172630.98822043.984659.21172044.796
675.33942046.343719.69042045.825  730.292046.348  739.852047.888767.33412054.307
#Mann= 4 ,-1 , 0
       0     .05       0  196.76    .045       0  211.37     .05       0
  730.29     .06       0
#XS Ineff= 2 , 0
          181.35 2042.27
Permanent Ineff=
       F       F
Bank Sta=196.76,211.37
XS Rating Curve= 0 ,0
Exp/Cntr(USF)=0,0
Exp/Cntr=0.3,0.1

Type RM Length L Ch R = 1 ,10043   ,146.6,158.9,164.2
XS GIS Cut Line= 4
2459239.11106477 619884.378032232459191.38831893619988.500386792
2459153.78857978620146.1300624482459077.14295767 620551.05033019
#Sta/Elev= 30
       0 2052.8815.964582053.65664.365972052.65986.366612051.683104.75742049.974
121.10772047.574141.66882043.654158.11762037.509  163.362034.097170.45432031.839
174.56652031.972  178.032034.095 182.7912037.168186.90322038.277191.0154 2038.48
232.13762037.636252.69872038.835330.28762040.056350.64272038.905368.84582040.015
 395.4242040.162423.92122038.813440.20532039.868591.34642040.939611.18852042.085
  636.362045.445651.89872047.853666.65432051.604680.39592052.971688.70032053.114
#Mann= 4 ,-1 , 0
       0     .05       0  163.36    .045       0  178.03     .05       0
  636.36     .06       0
#XS Ineff= 2 , 0
                          189.16         2040.38
Permanent Ineff=
       F       F
Bank Sta=163.36,178.03
XS Rating Curve= 0 ,0
Exp/Cntr(USF)=0,0
Exp/Cntr=0.5,0.3

Type RM Length L Ch R = 1 ,9885    ,52.5,53,53.1
XS GIS Cut Line= 4
2459228.98805807619887.2703198572459126.31184732619939.331497138
2458980.25132217620007.3002563662458767.66818161620133.114768128
#Sta/Elev= 30
       02051.763 69.92122045.978135.53872038.232163.17362036.833171.99742035.231
  184.422029.638 189.6452028.191 195.7552027.612198.76582027.729  204.68 2029.64
211.70442032.748216.83072034.167220.52822034.608260.23522034.357285.78192033.407
312.06122033.714  354.482033.166389.52482032.188417.1785 2032.01423.0184 2033.32
440.65332040.799  461.162041.087463.89742040.906466.81732041.462468.5416 2042.16
473.18962045.259477.83762047.176487.46462048.848501.07792052.452523.24542060.503
#Mann= 5 ,-1 , 0
       0     .05       0  184.42    .045       0  204.68     .05       0
  354.48     .06       0  461.16      .1       0
#XS Ineff= 2 , 0
             170  2034.7     219          2034.7
Permanent Ineff=
       F       F
Bank Sta=184.42,204.68
XS Rating Curve= 0 ,0
Exp/Cntr(USF)=0,0
Exp/Cntr=0.5,0.3

Type RM Length L Ch R = 1 ,9832    ,121.3,122.5,122.5
XS GIS Cut Line= 4
 2459223.3249589619852.8217280792459128.44346331619883.394654437
2458955.54829355619958.2456120732458733.10389833620055.235585347
#Sta/Elev= 30
       02051.469 34.22952047.72584.659832040.80894.27801 2039.01118.97132032.673
127.68882031.315162.55892031.104168.89442031.409176.64052032.506 179.9942032.149
  191.432027.947 197.4292026.661206.14662026.069   215.22027.946223.58162031.386
228.35212032.875241.01672032.198280.70492031.314310.78252031.674  346.232031.504
359.75842031.806411.14742030.338428.60222030.573437.32962031.556450.24152034.346
474.5515 2036.02480.96652037.743502.78492045.455517.09382051.722530.75742058.459
#Mann= 4 ,-1 , 0
       0     .05       0  191.43    .045       0   215.2     .05       0
  346.23     .06       0
#XS Ineff= 2 , 0
          174.67 2032.63  229.33         2033.05
Permanent Ineff=
       F       F
Bank Sta=191.43,215.2
XS Rating Curve= 0 ,0
Exp/Cntr(USF)=0,0
Exp/Cntr=0.5,0.3

Type RM Length L Ch R = 1 ,9709    ,124.4,124.4,124.2
XS GIS Cut Line= 4
2459209.26844103 619726.898755532459135.47172224619755.011791262
2458925.79533074619837.0081454792458648.17910289619958.831300317
#Sta/Elev= 30
       02042.76428.38282 2041.6845.504512039.72262.626182036.48684.045492030.235
101.2254 2028.07118.40532027.313169.9451 2026.83  200.012027.814206.0276 2027.13
  211.672024.934217.18992023.279221.46542023.095  233.272024.934247.25482030.868
260.13972028.893273.95392028.102310.88932029.117 332.1412028.241381.69942027.864
405.00372026.771434.1175 2027.28  454.572026.721 469.0632026.081499.11812027.813
511.26192030.717525.84932031.527530.21752033.112  557.142047.648607.27862072.395
#Mann= 5 ,-1 , 0
       0     .05       0  211.67    .045       0  233.27     .05       0
  454.57     .06       0  557.14      .1       0
#XS Ineff= 2 , 0
          182.78 2029.46  248.89         2031.17
Permanent Ineff=
       F       F
Bank Sta=211.67,233.27
XS Rating Curve= 0 ,0
Exp/Cntr(USF)=0,0
Exp/Cntr=0.3,0.1

Type RM Length L Ch R = 1 ,9585    ,103.4,103.3,102.8
XS GIS Cut Line= 4
2459225.53755893 619614.316459662459127.92285153619636.442460004
2458836.38025876619735.3586968382458560.45601917619851.194816288
#Sta/Elev= 30
       02036.12676.373362032.031143.57432025.333 168.9182024.836215.38162025.666
261.84522024.711282.96492025.877  289.862022.424295.63682020.006301.64522020.632
  306.172022.421312.53272025.971316.75662026.305337.87642024.593414.06862025.589
496.49422022.855518.18512023.243537.17832024.965 567.7332026.081570.78852026.612
579.95482030.928  585.922032.003604.94892032.284 609.2872033.244613.62522036.878
626.63982050.469 630.978 2053.23652.66892064.479  688.082080.874707.20972088.948
#Mann= 5 ,-1 , 0
       0     .05       0  289.86    .045       0  306.17     .05       0
  585.92     .06       0  688.08      .1       0
#XS Ineff= 2 , 0
          282.88 2028.26  311.66         2028.51
Permanent Ineff=
       F       F
Bank Sta=289.86,306.17
XS Rating Curve= 0 ,0
Exp/Cntr(USF)=0,0
Exp/Cntr=0.3,0.1

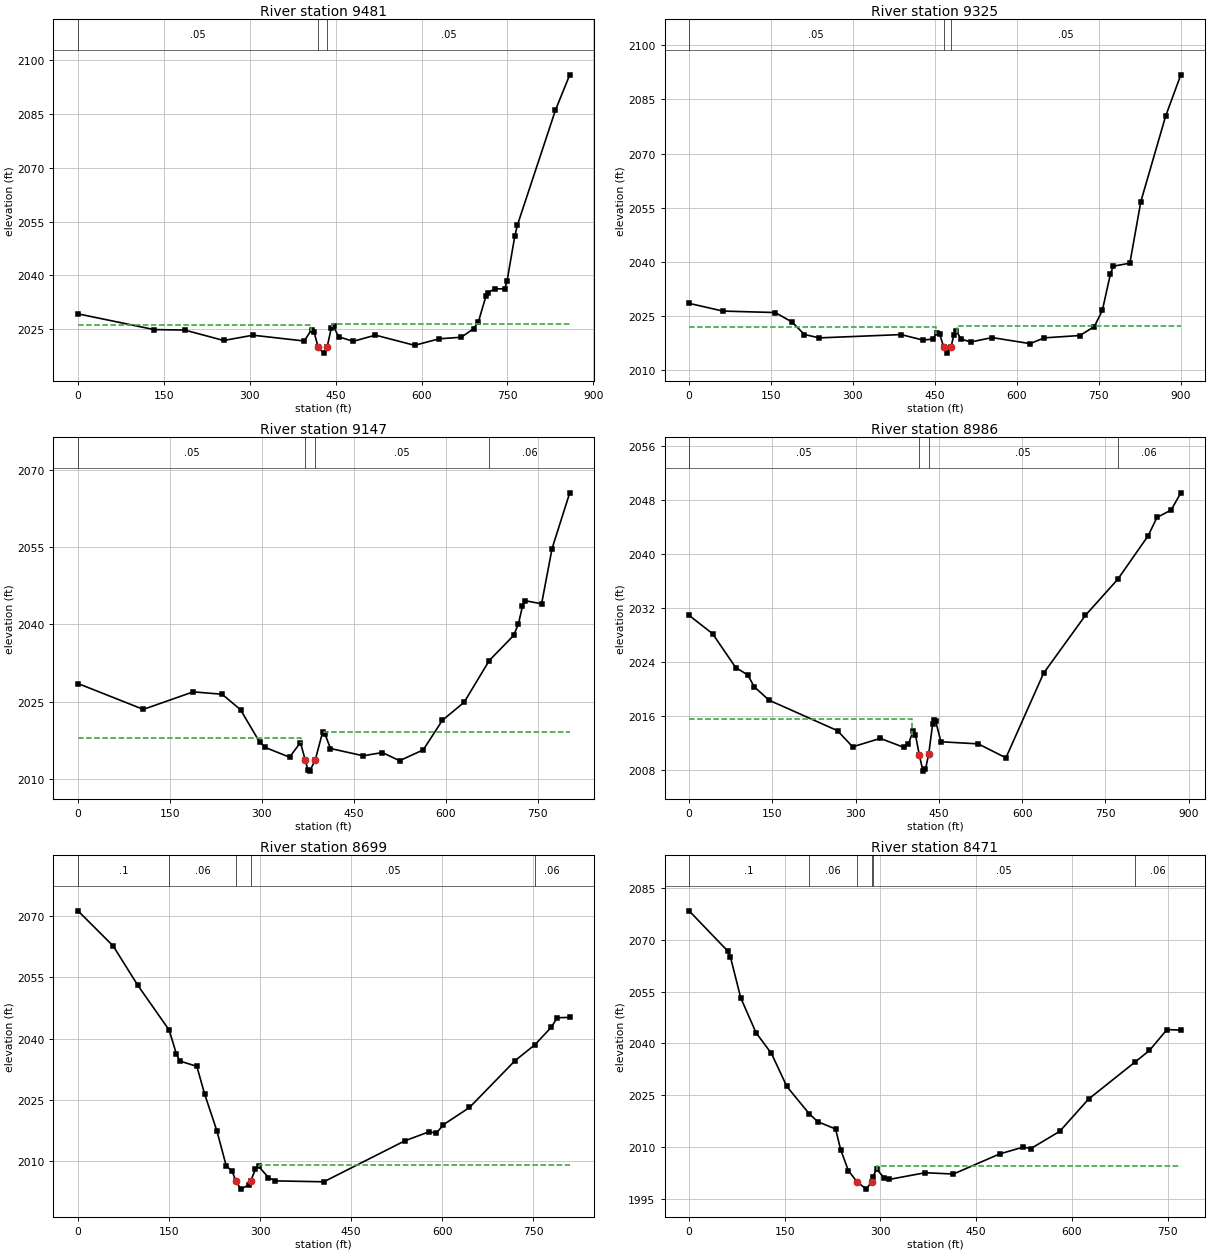
Type RM Length L Ch R = 1 ,9481    ,157.1,156.7,156.4
XS GIS Cut Line= 5
2459296.20852625619555.1906886932459173.07217063619505.354310445
2458950.74284668619585.889472811 2458642.2321665619704.794630799
2458502.43826454619780.315474386
#Sta/Elev= 30
       02029.322 132.8392024.942 186.3662024.808 254.4362021.905 305.4882023.375
 395.0242021.766 407.8842024.901 412.1712024.298 419.5862019.954 428.8692018.386
 435.0572020.039 442.1792025.261 446.4662025.828 455.0392022.938  480.762021.673
 519.3412023.397  587.932020.557 630.7982022.376  669.382022.807 690.8142025.163
 699.3872027.164 712.763 2034.41 715.8642035.219 727.6712036.262 745.3822036.298
 749.3642038.505 763.003 2051.07  767.552054.092 833.9342086.064 858.8262095.867
#Mann= 3 , 0 , 0
       0     .05       0 419.586    .045       0 435.057     .05       0
#XS Ineff= 2 , 0
          406.67 2026.34  444.44         2026.51
Permanent Ineff=
       F       F
Bank Sta=419.586,435.057
XS Rating Curve= 0 ,0
Exp/Cntr(USF)=0,0
Exp/Cntr=0.3,0.1

Type RM Length L Ch R = 1 ,9325    ,178.4,177.9,177.5
XS GIS Cut Line= 5
2459145.02762891619167.4368205782459098.10701696619327.400284548
 2458875.2220031619446.0955708512458576.35228167619574.641687595
 2458452.6266443619669.444448694
#Sta/Elev= 30
       0 2028.55  61.9592026.419 157.8352026.008 188.6392023.364 211.2982019.926
  238.49    2019  388.042019.911 428.4512018.393 445.8682018.675 454.5762020.485
 458.9312020.068 465.8622016.583 471.9942014.782 479.7392016.611 485.0562019.917
 489.4112020.856 498.1192018.694 515.5372017.844 554.7252019.086 624.3942017.411
  650.522019.008  715.532019.655  741.96 2022.12 756.6682026.577 771.5672036.735
 776.8252038.842  807.062039.658 827.2172056.726  872.572080.339 900.4352091.784
#Mann= 3 , 0 , 0
       0     .05       0 465.862    .045       0 479.739     .05       0
#XS Ineff= 2 , 0
          452.64 2022.03  491.01         2022.16
Permanent Ineff=
       F       F
Bank Sta=465.862,479.739
XS Rating Curve= 0 ,0
Exp/Cntr(USF)=0,0
Exp/Cntr=0.3,0.1

Type RM Length L Ch R = 1 ,9147    ,160.9,160.7,160.3
XS GIS Cut Line= 4
2459094.22770068619164.6942798212458843.56277303619261.103867378
2458488.45412553619434.6411249822458403.29232319619543.905324214
#Sta/Elev= 30
       02028.523106.53612023.501188.01472026.906235.15692026.438265.15652023.438
296.18872017.172305.09292016.125345.16162014.214362.96992017.057  370.612013.694
375.18482011.763378.17542011.502  387.13 2013.69399.10972019.074403.03872018.679
411.94292015.897465.36792014.483496.53252015.112524.71532013.531563.31372015.636
594.47832021.375 630.095 2024.89  670.952032.988710.80632037.865718.64382040.117
725.15062043.528730.05512044.603756.40762044.017773.5081 2054.76802.3417 2065.58
#Mann= 4 ,-1 , 0
       0     .05       0  370.61    .045       0  387.13     .05       0
  670.95     .06       0
#XS Ineff= 2 , 0
          363.33 2017.95  401.11         2019.06
Permanent Ineff=
       F       F
Bank Sta=370.61,387.13
XS Rating Curve= 0 ,0
Exp/Cntr(USF)=0,0
Exp/Cntr=0.3,0.1

Type RM Length L Ch R = 1 ,8986    ,289.8,286.8,281
XS GIS Cut Line= 4
2459047.47103445618959.3378908512458864.96728846619064.475918434
2458438.46396902619290.6218645562458329.35846869619449.320774116
#Sta/Elev= 30
       02030.88642.384352028.16983.930852023.158105.64642022.075117.36222020.314
143.94252018.327267.46742013.805294.63252011.412344.43512012.663386.55162011.353
395.09042011.783403.40932013.763407.82022013.206  414.742010.216421.40272007.815
425.93032008.129  431.69 2010.31438.91382014.858441.87252015.328444.04032015.294
453.70732012.164 521.0082011.852570.81052009.783638.72322022.319714.05692030.892
  772.21 2036.22827.02562042.673842.94172045.386868.44642046.492885.9575 2049.04
#Mann= 4 ,-1 , 0
       0     .05       0  414.74    .045       0  431.69     .05       0
  772.21     .06       0
#XS Ineff= 2 , 0
          401.11  2015.6  443.33         2015.27
Permanent Ineff=
       F       F
Bank Sta=414.74,431.69
XS Rating Curve= 0 ,0
Exp/Cntr(USF)=0,0
Exp/Cntr=0.3,0.1

Type RM Length L Ch R = 1 ,8699    ,234.1,228.3,218.2
XS GIS Cut Line= 4
2458728.08947896618721.2895265112458591.21166947618856.183599637
2458392.83803252 619078.362073022458269.84637761619373.938792075
#Sta/Elev= 30
       02071.16458.047722062.57198.252132053.041  150.292042.042161.84222036.341
167.54082034.517195.80622033.207208.58952026.466228.91272017.411244.06762008.982
253.91682007.591  259.942005.327268.08162003.242281.60432004.287  284.83 2005.32
 292.3292008.117297.69142008.774313.77852006.072324.74072005.257 404.9392005.031
538.25812015.014578.77142017.255590.24772016.869602.17272018.986645.00462023.166
 720.222 2034.62  752.412038.431779.61932042.726789.54162045.061810.17272045.168
#Mann= 5 ,-1 , 0
       0      .1       0  150.29     .06       0  259.94    .045       0
  284.83     .05       0  752.41     .06       0
#XS Ineff= 2 , 0
                          297.78         2009.13
Permanent Ineff=
       F       F
Bank Sta=259.94,284.83
XS Rating Curve= 0 ,0
Exp/Cntr(USF)=0,0
Exp/Cntr=0.3,0.1

Type RM Length L Ch R = 1 ,8471    ,264.3,261.5,259.5
XS GIS Cut Line= 4
2458347.21209602618586.3954533852458327.37473232618788.736563074
2458303.56989589619062.4921820642458240.09033207619348.150219272
#Sta/Elev= 30
       02078.34760.785462066.67364.804632064.99980.881342053.214104.99642043.073
129.11152037.085153.22652027.543  187.962019.727201.45672017.387229.56422015.241
237.59442009.256249.63972003.207  262.952000.024277.74531997.858  286.332000.025
  288.432001.454293.80572003.675 305.8512001.082313.88122000.674370.09252002.602
414.25852002.223486.70342008.027523.58162010.005535.87432009.607580.94772014.574
 626.0212023.886  699.222034.655721.61042037.976748.94822043.996770.72622043.854
#Mann= 6 ,-1 , 0
       0      .1       0  187.96     .06       0  262.95    .045       0
  286.33     .06       0  288.43     .05       0  699.22     .06       0
#XS Ineff= 2 , 0
                          295.11          2004.5
Permanent Ineff=
       F       F
Bank Sta=262.95,286.33
XS Rating Curve= 0 ,0
Exp/Cntr(USF)=0,0
Exp/Cntr=0.3,0.1

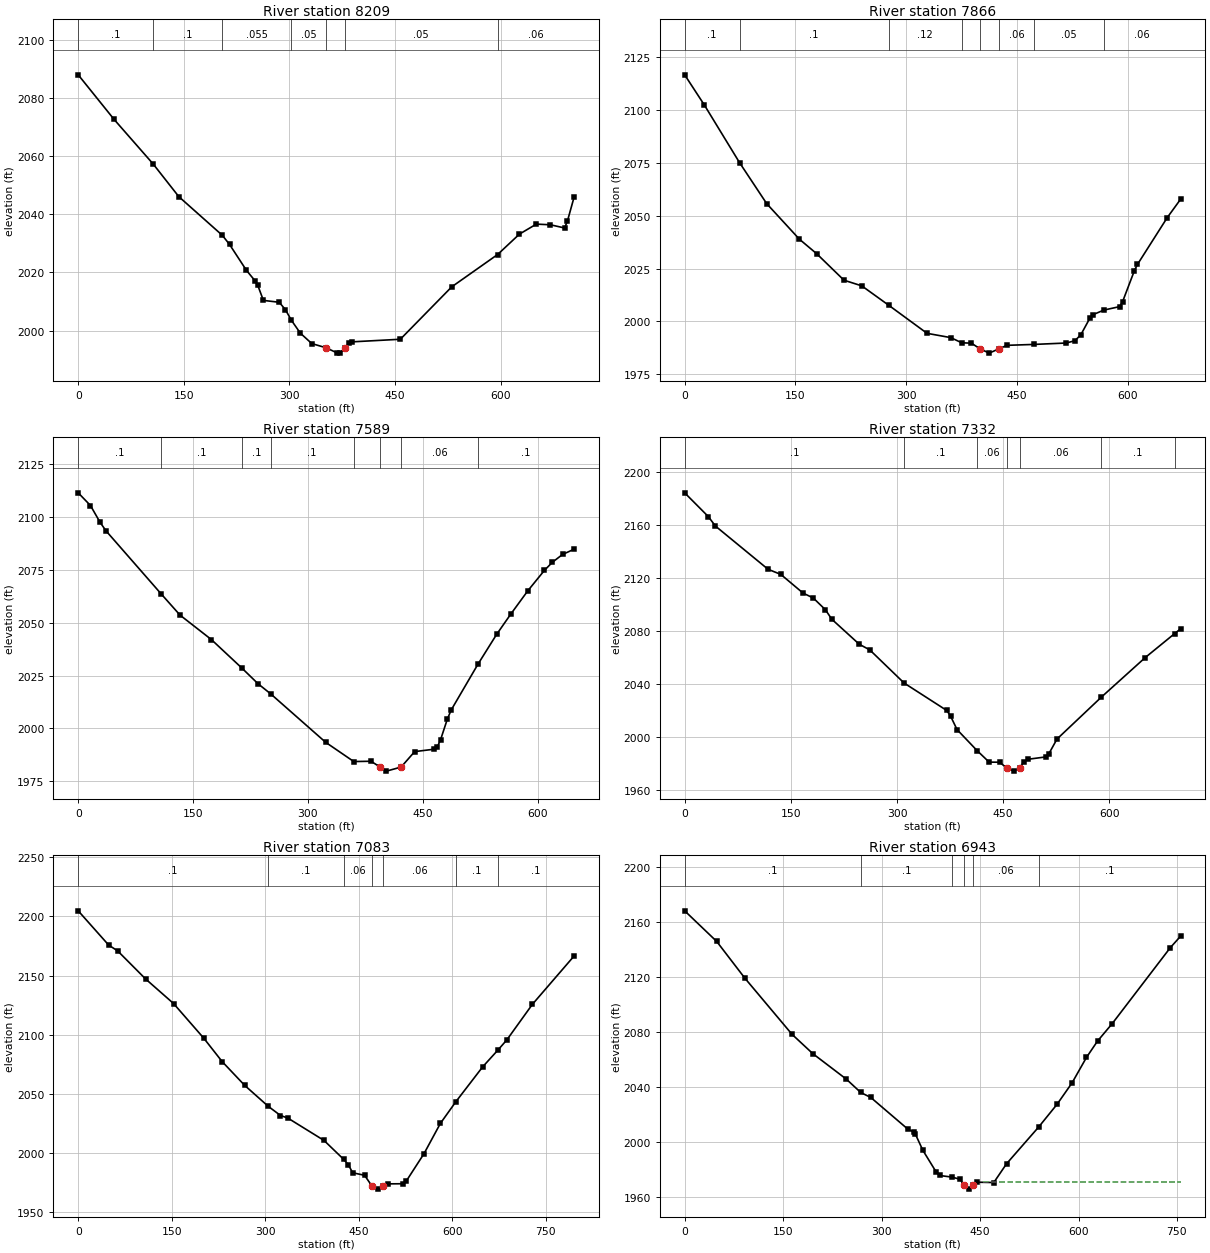
Type RM Length L Ch R = 1 ,8209    ,341,343.1,343.9
XS GIS Cut Line= 4
2458065.52153155 618608.216553452458079.40768614618887.923381549
 2458121.0661499619133.9066913662458130.98483174619308.475491882
#Sta/Elev= 30
       02087.94450.736732072.677  106.752057.199  142.852046.077  204.82 2032.74
214.93872029.627238.96832020.712 250.983 2017.18 254.9882015.603262.99782010.399
285.5198 2009.75 294.2522007.223  302.772003.567315.51671999.122331.74451995.553
  352.281994.086368.25711992.267372.3141 1992.38   378.61994.087 384.4851995.768
388.5419 1996.14457.51021997.036 530.5232015.055   595.72026.173626.67782033.186
650.71662036.622670.74882036.388690.78112035.292694.78752037.615704.38762045.983
#Mann= 7 ,-1 , 0
       0      .1       0  106.75      .1       0  204.82    .055       0
  302.77     .05       0  352.28    .045       0   378.6     .05       0
   595.7     .06       0
Bank Sta=352.28,378.6
XS Rating Curve= 0 ,0
Exp/Cntr(USF)=0,0
Exp/Cntr=0.3,0.1

Type RM Length L Ch R = 1 ,7866    ,269.8,277.3,284.7
XS GIS Cut Line= 4
2457781.84723071618588.3791897552457748.12371243618891.890854288
2457763.99360339619137.8741641052457748.12371243619256.898346275
#Sta/Elev= 30
       02116.77926.674842102.479   74.372075.182111.19182055.757155.46252038.937
 178.9472032.045215.83182019.537239.97952016.852  276.482007.669328.42731994.375
360.49381992.356   375.31989.908 388.552 1989.72  399.831987.116412.60191985.007
  426.241987.116436.65181988.699  473.221989.129516.81811989.789528.84311990.893
536.85971993.773548.88462001.495552.89982003.158  567.75 2005.37589.49712007.045
593.25382009.303609.39542024.124613.43082026.975653.78492049.152671.95172057.892
#Mann= 8 ,-1 , 0
       0      .1       0   74.37      .1       0  276.48     .12       0
   375.3     .06       0  399.83    .045       0  426.24     .06       0
  473.22     .05       0  567.75     .06       0
Bank Sta=399.83,426.24
XS Rating Curve= 0 ,0
Exp/Cntr(USF)=0,0
Exp/Cntr=0.3,0.1

Type RM Length L Ch R = 1 ,7589    ,255.6,257.3,259.4
XS GIS Cut Line= 4
2457730.27008511618594.3303988632457547.76633911618826.427554094
2457440.64457516619022.8174546742457379.14874771619135.890427736
#Sta/Elev= 30
       02111.26315.978522105.276 28.54682097.33436.33255  2093.3  108.252063.567
133.01422053.511173.82492042.002  214.15 2028.38234.78432021.138  251.282016.364
323.12291993.478  359.881984.381382.35541984.525  394.361981.771402.48741979.861
  421.651981.773439.39611989.077464.4002 1990.19468.9261 1991.26473.24491994.709
482.08962004.455487.15152008.759  521.862030.235546.36572044.391564.57892053.832
587.34542065.095608.89592074.667619.21852078.469632.49032082.156647.67612084.656
#Mann= 8 ,-1 , 0
       0      .1       0  108.25      .1       0  214.15      .1       0
  251.28      .1       0  359.88     .06       0  394.36    .045       0
  421.65     .06       0  521.86      .1       0
Bank Sta=394.36,421.65
XS Rating Curve= 0 ,0
Exp/Cntr(USF)=0,0
Exp/Cntr=0.3,0.1

Type RM Length L Ch R = 1 ,7332    ,247.8,249.2,250.4
XS GIS Cut Line= 4
 2457561.6524937618399.9242346532457349.39270216618689.549744599
2457224.41731089618860.1510723762457145.06785611 618963.30536359
#Sta/Elev= 30
       02184.30733.433282166.331 43.35172159.234117.73982126.548135.84712122.645
167.33192108.499181.63642104.848198.80742095.965207.92162088.745246.67922069.863
261.55682065.586  310.012040.556370.32722019.796375.61612015.611384.8275 2005.36
  413.121989.498 430.1591980.777445.03441980.707  454.881976.368464.86821973.973
  473.131976.368479.27111980.995 484.7021982.914510.75231984.745514.45281987.006
526.00691998.193   588.42029.744650.71862059.797  692.132077.871700.70072081.529
#Mann= 7 ,-1 , 0
       0      .1       0  310.01      .1       0  413.12     .06       0
  454.88    .045       0  473.13     .06       0   588.4      .1       0
  692.13      .1       0
Bank Sta=454.88,473.13
XS Rating Curve= 0 ,0
Exp/Cntr(USF)=0,0
Exp/Cntr=0.3,0.1

Type RM Length L Ch R = 1 ,7083    ,139.8,139.5,138.9
XS GIS Cut Line= 4
 2457470.4006207618257.095216049 2457190.6937926618518.948416822
2457018.10872846618695.500953708 2456905.0357554618816.508872247
#Sta/Elev= 30
       02204.77648.841832175.83963.285942170.909107.97932147.256152.94842126.439
201.62542097.028230.88972077.381267.04332057.282  304.842039.577324.53582031.809
336.24162029.658394.38632010.715  425.811994.788433.41121990.171440.2979 1983.42
459.44431981.277  471.431972.052480.35371969.587  488.541972.053497.52041974.038
520.40941974.132526.13161976.235554.74291999.524581.07462025.164  606.032043.561
648.97082072.972  673.452087.165687.69742095.738728.70832125.789795.65762166.672
#Mann= 7 ,-1 , 0
       0      .1       0  304.84      .1       0  425.81     .06       0
  471.43    .045       0  488.54     .06       0  606.03      .1       0
  673.45      .1       0
Bank Sta=471.43,488.54
XS Rating Curve= 0 ,0
Exp/Cntr(USF)=0,0
Exp/Cntr=0.5,0.3

Type RM Length L Ch R = 1 ,6943    ,98.8,99.7,99.6
XS GIS Cut Line= 4
2457336.98782336618180.1587980272457075.77086635618429.661990146
2456978.54661778618550.3137684952456811.03977988618721.334735863
#Sta/Elev= 30
       02168.44648.785422146.15891.60505 2119.47163.51422078.553 195.0642064.527
246.48632045.824  268.242036.189283.60662032.549339.84322009.572348.67762007.453
351.50672005.842362.86361994.107382.74531978.637388.36331975.782  407.581974.566
419.31481973.037  426.081968.676432.98791965.843  439.081968.675445.73781970.888
470.93191970.643490.36241984.306  539.182010.996567.37752027.632590.20932043.221
612.16982061.762628.9669 2073.61 651.3632086.342739.90392141.654755.56652149.999
#Mann= 6 ,-1 , 0
       0      .1       0  268.24      .1       0  407.58     .06       0
  426.08    .045       0  439.08     .06       0  539.18      .1       0
#XS Ineff= 2 , 0
           409.1  1971.4  454.97         1971.34
Permanent Ineff=
       F       F
Bank Sta=426.08,439.08
XS Rating Curve= 0 ,0
Exp/Cntr(USF)=0,0
Exp/Cntr=0.5,0.3