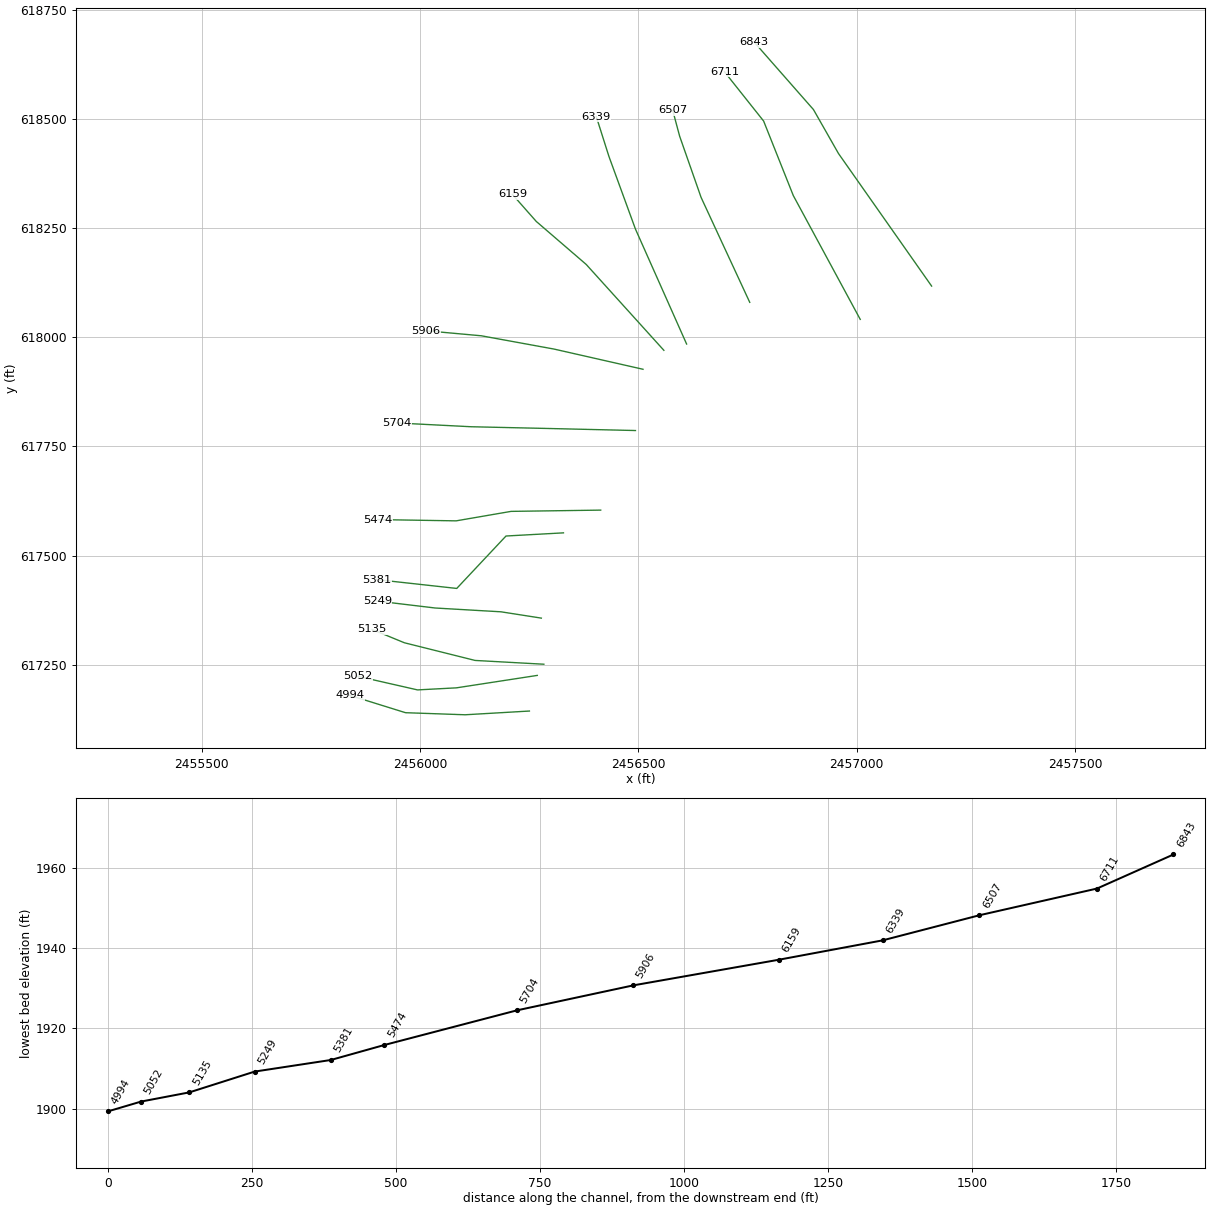
HEC-RAS study DRYRN1.prj: DRYRN1

--- DRYRN1.g01 (geometry) --- (continued)

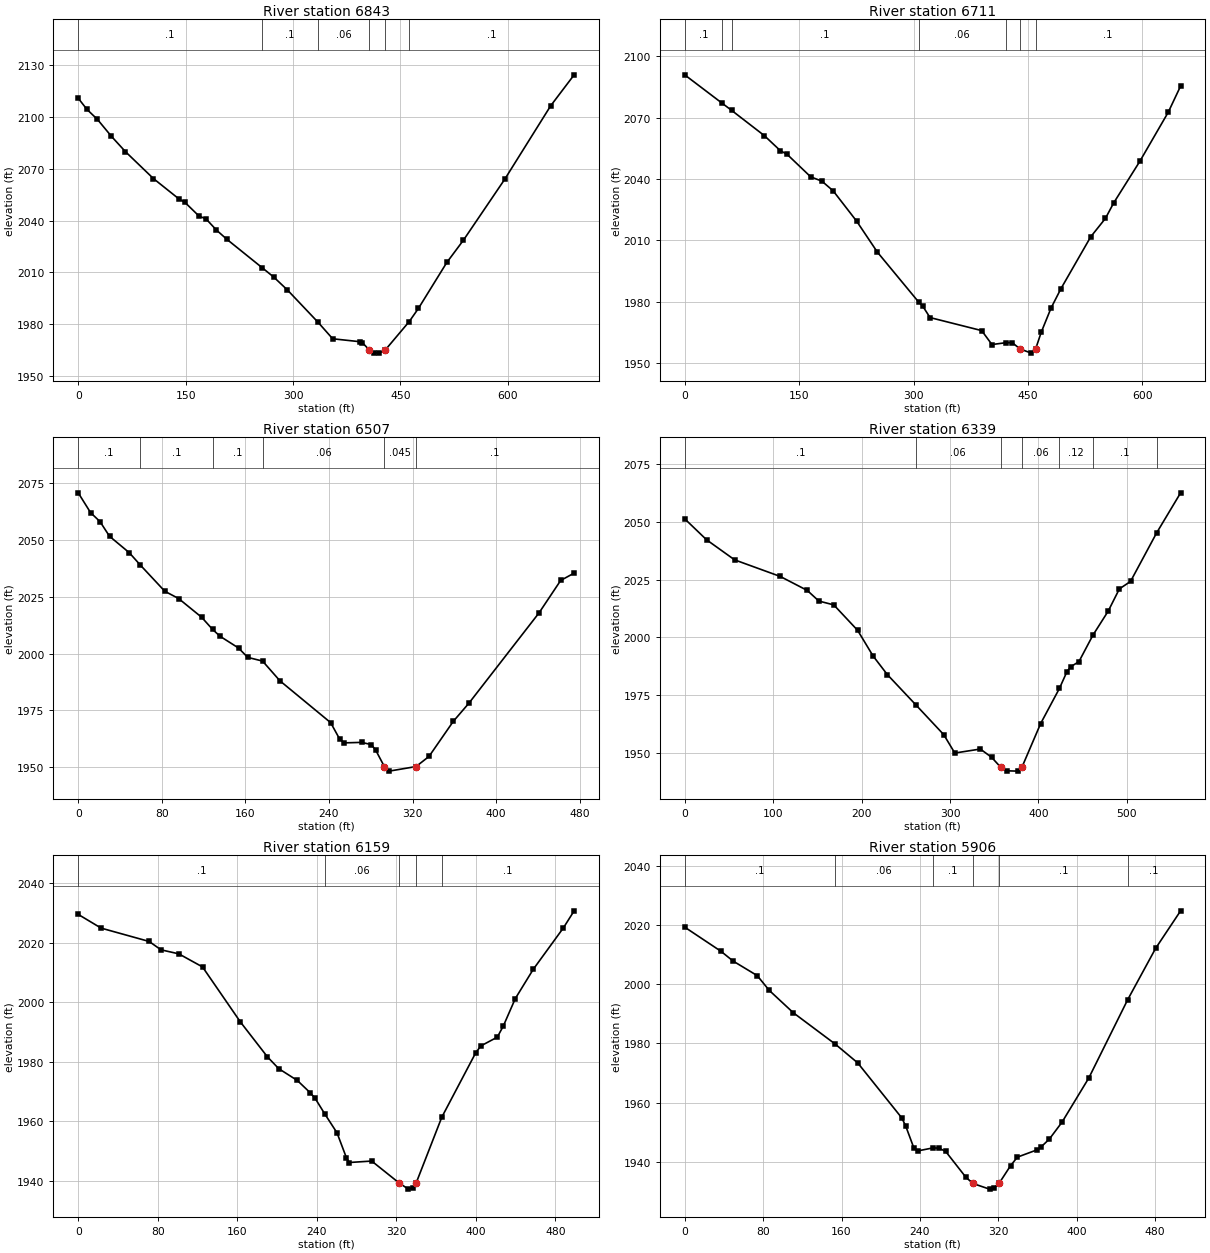
Type RM Length L Ch R = 1 ,6843    ,133.4,132.8,130.1
XS GIS Cut Line= 4
2457171.82373844 618116.904467632456958.63321747618420.290978235
2456901.23576952618521.0293562742456765.35609682618675.651052799
#Sta/Elev= 30
       02110.65412.205462104.20826.871952098.40646.42727 2088.6265.982592079.772
105.09322064.209141.01982052.351149.09272050.457168.73082042.542178.42572040.951
193.09222034.456207.75872029.077  256.782012.754273.20622007.257292.19311999.841
  334.831981.238355.35991971.656393.15461969.971396.8121  1969.4  406.371965.261
413.68371963.594419.8307 1963.36  428.971965.259  462.321981.631475.07521989.189
514.75522015.749 538.011 2028.66595.72332063.883659.88622106.335692.58642124.181
#Mann= 6 ,-1 , 0
       0      .1       0  256.78      .1       0  334.83     .06       0
  406.37    .045       0  428.97     .06       0  462.32      .1       0
Bank Sta=406.37,428.97
XS Rating Curve= 0 ,0
Exp/Cntr(USF)=0,0
Exp/Cntr=0.5,0.3

Type RM Length L Ch R = 1 ,6711    ,204.1,204,202.1
XS GIS Cut Line= 4
2457008.36610321618040.678227228  2456855.074859618324.122414647
2456787.10609977618494.7673846242456697.44518334618607.566602066
#Sta/Elev= 30
       02090.973   49.482076.973   61.512073.595104.31062061.267125.29792053.909
134.3929 2052.04165.15322041.078179.86782038.971194.66672034.211225.34282019.424
252.62782004.231  306.521979.907311.74521977.998 321.5751972.251389.28791965.879
402.72141959.057  420.951959.961429.31711959.995  439.571956.898454.38891954.862
  459.981956.899467.30571965.065480.22261976.934493.13941986.378 532.2172011.767
 551.5022020.772562.28792028.331596.50042048.634633.82392072.698650.01622085.507
#Mann= 7 ,-1 , 0
       0      .1       0   49.48      .1       0   61.51      .1       0
  306.52     .06       0  420.95      .1       0  439.57    .045       0
  459.98      .1       0
Bank Sta=439.57,459.98
XS Rating Curve= 0 ,0
Exp/Cntr(USF)=0,0
Exp/Cntr=0.3,0.1

Type RM Length L Ch R = 1 ,6507    ,168.3,167.9,167.9
XS GIS Cut Line= 4
2456755.29093587618079.7241101892456643.93786225618319.783983207
2456594.76897259618460.0599331032456578.86139064618519.351829451
#Sta/Elev= 30
       02070.84411.832282062.12520.868782058.15529.947112051.71148.82694 2044.48
   59.192039.14482.859622027.47396.087742024.263118.13462016.008   128.62010.651
135.77212007.631153.40962002.467162.2284 1998.33  176.441996.707 193.0941987.989
241.59711969.579250.4159 1962.17254.82521960.655271.14071960.877280.63651959.894
284.87521957.323     2931950.223 297.5911948.206  323.351950.222335.7384 1954.68
 359.0191970.156373.88591978.114441.05192017.944461.75922032.231474.66092035.472
#Mann= 6 ,-1 , 0
       0      .1       0   59.19      .1       0   128.6      .1       0
  176.44     .06       0     293    .045       0  323.35      .1       0
Bank Sta=293,323.35
XS Rating Curve= 0 ,0
Exp/Cntr(USF)=0,0
Exp/Cntr=0.3,0.1

Type RM Length L Ch R = 1 ,6339    ,173.8,180,185.3
XS GIS Cut Line= 4
2456610.67655454617984.2786185072456493.53890566618247.476792539
2456432.80086549618413.7833310752456403.87798923618504.890391317
#Sta/Elev= 30
       0 2051.36 24.75062042.25756.463632033.551107.97062026.375138.5854  2020.3
151.7202 2015.69168.56712014.031195.5028 2003.01213.0159 1991.87229.16361983.786
   261.61970.583292.92871957.751305.40561949.787334.30651951.526347.08181947.911
  357.111943.709364.11541942.076376.89071941.945  381.391943.709402.44121962.551
  423.671977.783432.25021985.113436.50861987.209445.77071989.438  461.54 2000.88
478.89062011.359491.48082020.966 504.071 2024.19  533.522045.193560.72632062.619
#Mann= 7 ,-1 , 0
       0      .1       0   261.6     .06       0  357.11    .045       0
  381.39     .06       0  423.67     .12       0  461.54      .1       0
  533.52     .12       0
Bank Sta=357.11,381.39
XS Rating Curve= 0 ,0
Exp/Cntr(USF)=0,0
Exp/Cntr=0.3,0.1

Type RM Length L Ch R = 1 ,6159    ,245.1,253,257.7
XS GIS Cut Line= 4
2456558.61537726617969.8171803732456380.73968821 618166.49273899
2456266.49432696618264.8305182992456211.54086205618327.014702273
#Sta/Elev= 30
       02029.51823.020762024.906 71.36622020.41383.292782017.603101.1826 2016.25
125.03582011.852163.2458  1993.3190.41151981.582201.73951977.631220.44851973.659
233.35831969.543238.33831967.658   247.81962.535260.32471956.067269.71411947.752
272.55051946.072295.2412 1946.56  322.591939.252332.11351937.119336.42351937.482
  340.05 1939.25  365.761961.308399.75641982.889405.03411985.289421.5823 1988.23
427.62281991.956439.70372001.206457.82522011.076488.02772024.957498.90692030.717
#Mann= 5 ,-1 , 0
       0      .1       0   247.8     .06       0  322.59    .045       0
  340.05     .06       0  365.76      .1       0
Bank Sta=322.59,340.05
XS Rating Curve= 0 ,0
Exp/Cntr(USF)=0,0
Exp/Cntr=0.3,0.1

Type RM Length L Ch R = 1 ,5906    ,198.8,202.1,201.9
XS GIS Cut Line= 4
2456510.89263142617926.4328659722456306.98635373   617972.709468
 2456140.6798152 618003.078488082456013.41915962618014.647638587
#Sta/Elev= 30
       02019.32637.066822011.14449.371982007.856 73.98232002.93486.287451997.927
110.82581990.368  153.621979.758176.52531973.406221.53531954.777225.60151951.946
233.73381944.696237.79991943.641  253.061944.645259.31011944.588266.26291943.458
286.59371934.844  293.931932.635310.99051930.714315.05671930.969  320.691932.635
332.56991938.703339.45351941.539359.78431944.038363.85041945.071371.9827 1947.63
384.91061953.341412.22291968.276  451.891994.758480.50342012.182505.9337 2024.84
#Mann= 6 ,-1 , 0
       0      .1       0  153.62     .06       0  253.06      .1       0
  293.93    .045       0  320.69      .1       0  451.89      .1       0
Bank Sta=293.93,320.69
XS Rating Curve= 0 ,0
Exp/Cntr(USF)=0,0
Exp/Cntr=0.3,0.1

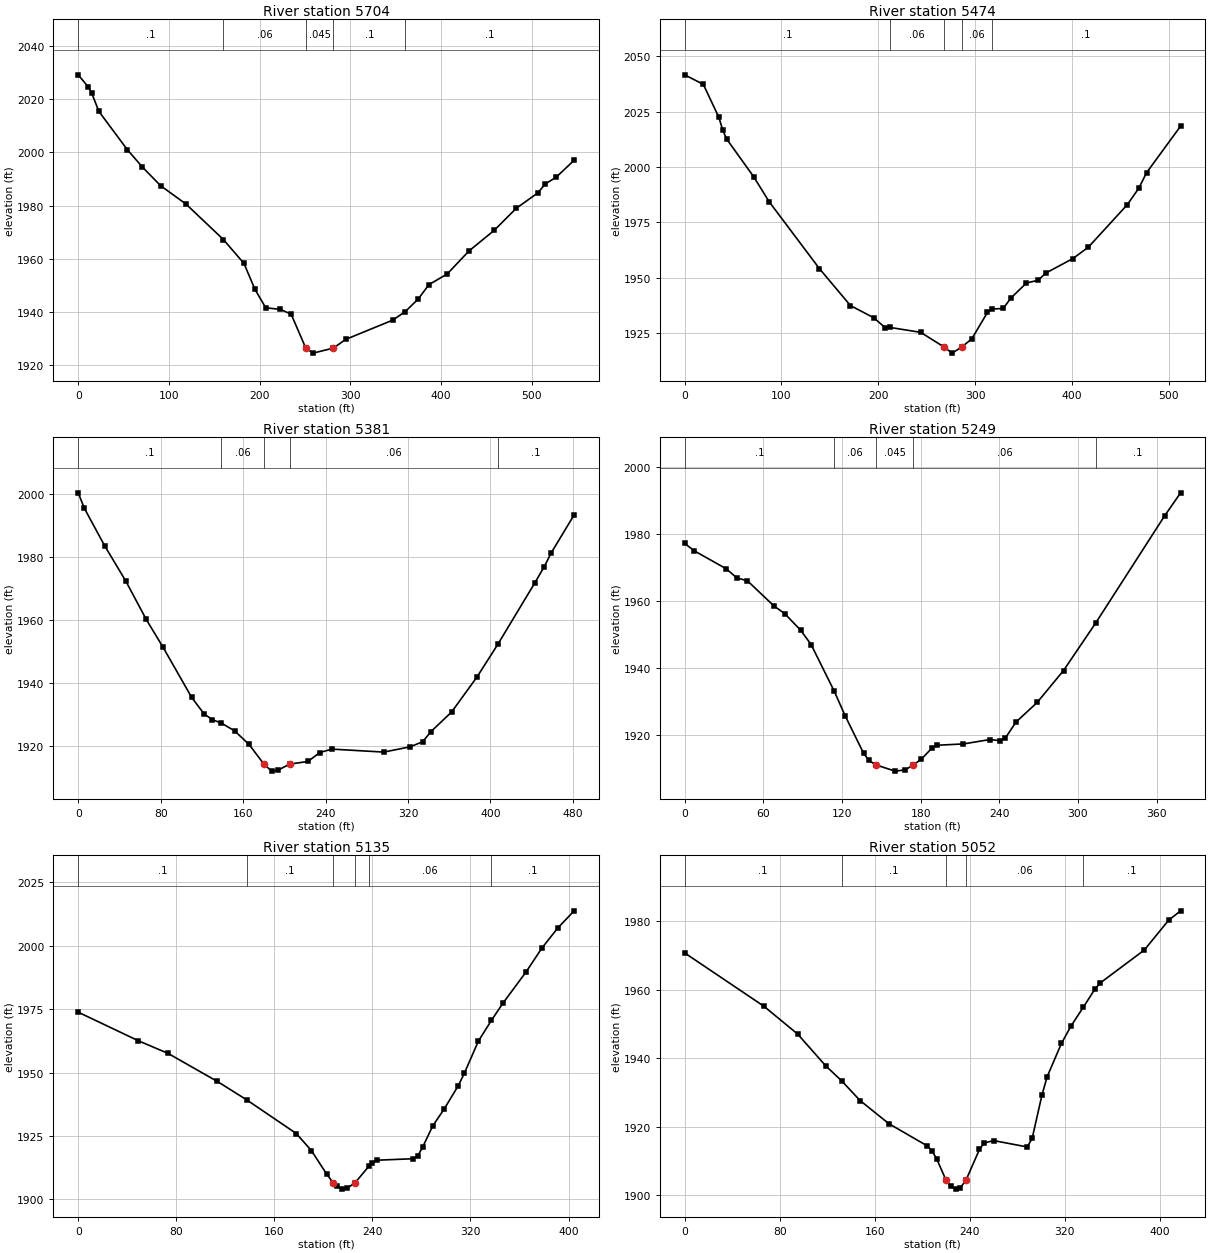
Type RM Length L Ch R = 1 ,5704    ,229.3,229.6,226.9
XS GIS Cut Line= 4
2456493.53890566617786.1569160762456309.87864136617790.495347516
2456117.54151418617794.833778956 2455946.8965442617803.510641836
#Sta/Elev= 30
       02029.20211.264942024.58814.797992022.40222.800222015.43954.261542000.994
70.813611994.48990.81919  1987.5 118.8271980.579  160.151967.214182.8449 1958.21
194.84791948.518 206.8511941.531222.8551 1940.96234.85811939.129  250.971926.375
258.86421924.478  281.471926.374294.87341929.625346.88661936.897  360.691940.103
374.80751944.776 386.9081950.279406.93381954.252430.96481962.928458.85531970.694
 483.032 1978.96 507.0631984.812515.07341988.148527.08891990.646 546.9631997.067
#Mann= 5 ,-1 , 0
       0      .1       0  160.15     .06       0  250.97    .045       0
  281.47      .1       0  360.69      .1       0
Bank Sta=250.97,281.47
XS Rating Curve= 0 ,0
Exp/Cntr(USF)=0,0
Exp/Cntr=0.5,0.3

Type RM Length L Ch R = 1 ,5474    ,85.6,93.1,100.2
XS GIS Cut Line= 4
2456414.00099592617603.9427955922456208.64857442617601.050507966
2456082.83406266617579.358350765 2455903.5122298617582.250638392
#Sta/Elev= 30
       0  2041.619.25787 2037.2835.259452022.46539.259852016.68843.260252012.657
71.263021995.57387.264611984.276139.26981953.997171.27291937.349195.27531931.842
207.30441927.308  212.111927.461243.83561925.244  267.98 1918.62276.30771915.855
   286.3 1918.62296.60281922.291312.8389 1934.26  317.141935.756 329.0751936.036
337.13321940.783353.13531947.561365.13681948.763373.13781952.032401.14151958.602
417.14361963.756457.1488 1982.85469.15031990.334477.15141997.349512.38882018.437
#Mann= 5 ,-1 , 0
       0      .1       0  212.11     .06       0  267.98    .045       0
   286.3     .06       0  317.14      .1       0
#XS Ineff= 2 , 0
             240    1922     312            1922
Permanent Ineff=
       F       F
Bank Sta=267.98,286.3
XS Rating Curve= 0 ,0
Exp/Cntr(USF)=0,0
Exp/Cntr=0.5,0.3

Type RM Length L Ch R = 1 ,5381    ,139.7,132.1,123.6
XS GIS Cut Line= 4
2456328.67851093617551.8816183112456197.07942392617544.650899244
2456084.28020647617424.6209627352455900.61994218617444.866976122
#Sta/Elev= 30
       02000.4345.9424211995.53725.560411983.68246.002751972.52866.032921960.241
82.057051951.577110.09931935.508122.11741930.281130.12951928.454   138.91927.355
151.67291924.913165.82191920.567   180.21914.343187.77521912.109193.61611912.353
  205.121914.343 222.8211915.165 234.5031918.012246.18491919.094 296.5121918.152
322.2019 1919.83334.27461921.438 342.3231924.654362.44421930.903386.95191941.969
  407.131952.314442.92881971.752452.19591976.953459.02571981.376481.28491993.453
#Mann= 5 ,-1 , 0
       0      .1       0   138.9     .06       0   180.2    .045       0
  205.12     .06       0  407.13      .1       0
Bank Sta=180.2,205.12
XS Rating Curve= 0 ,0
Exp/Cntr(USF)=0,0
Exp/Cntr=0.5,0.3

Type RM Length L Ch R = 1 ,5249    ,117.7,113.4,110
XS GIS Cut Line= 4
2456278.06347746617356.6522035072456185.51027341617371.113641641
2456035.11131682617379.7905045212455902.06608599617395.698086468
#Sta/Elev= 30
       01977.2057.4072351974.97131.698441969.63539.795511966.90847.892571966.032
68.135241958.52576.23231 1956.2788.377911951.34596.446021947.009  114.111933.072
122.60071925.588136.51251914.527140.51921912.397  145.831911.084160.55241909.221
 168.0581909.569  174.521911.085180.58571912.812 188.599 1916.09192.60571916.946
212.63891917.344232.67221918.634240.68551918.329244.69411919.144252.75111923.874
268.86511929.712289.00751939.263   313.51953.428366.18641985.482378.31811992.312
#Mann= 5 ,-1 , 0
       0      .1       0  114.11     .06       0  145.83    .045       0
  174.52     .06       0   313.5      .1       0
Bank Sta=145.83,174.52
XS Rating Curve= 0 ,0
Exp/Cntr(USF)=0,0
Exp/Cntr=0.3,0.1

Type RM Length L Ch R = 1 ,5135    ,81.5,83.7,86.3
XS GIS Cut Line= 4
2456283.84805272617251.0837051322456126.21837706617259.760568012
2455964.25026996617300.2525947862455890.49693548617330.621614867
#Sta/Elev= 30
       01973.77649.177351962.48973.213681957.554113.27421946.544  137.381939.242
 177.9411925.947190.31031919.173202.67961909.973   208.11906.503210.92581905.077
215.04891904.035 219.1721904.357  225.771906.503  237.091913.017239.78761914.461
243.91071915.438272.77241916.011276.89551917.015281.01861920.628289.26481928.989
298.55171935.618309.88031944.666315.04411949.742326.44911962.372  337.041970.513
  346.381977.247365.38151989.662 378.3591999.103391.33652007.019404.58232013.726
#Mann= 6 ,-1 , 0
       0      .1       0  137.38      .1       0   208.1    .045       0
  225.77      .1       0  237.09     .06       0  337.04      .1       0
Bank Sta=208.1,225.77
XS Rating Curve= 0 ,0
Exp/Cntr(USF)=0,0
Exp/Cntr=0.3,0.1

Type RM Length L Ch R = 1 ,5052    ,58.6,57.9,57.3
XS GIS Cut Line= 4
2456268.69203171617225.490719609 2456083.6731153617197.026270931
2455994.48450944617192.2821961512455856.90634083617223.593089697
#Sta/Elev= 30
       01970.81166.722861955.21295.052291947.111118.79161937.787  132.18 1933.41
147.66411927.655171.94641920.879204.14771914.409208.15341912.975 212.159  1910.6
  220.111904.343 224.176 1902.55228.18161901.743232.18731902.183  236.85 1904.34
248.20991913.343252.2155 1915.23260.22691915.933  288.551914.068292.65231916.661
300.8569 1929.27305.20611934.597 317.2661944.365325.47061949.526  335.651954.916
345.30711960.163350.08431962.073387.00481971.651407.51621980.371417.6065 1983.12
#Mann= 5 ,-1 , 0
       0      .1       0  132.18      .1       0  220.11    .045       0
  236.85     .06       0  335.65      .1       0
Bank Sta=220.11,236.85
XS Rating Curve= 0 ,0
Exp/Cntr(USF)=0,0
Exp/Cntr=0.3,0.1

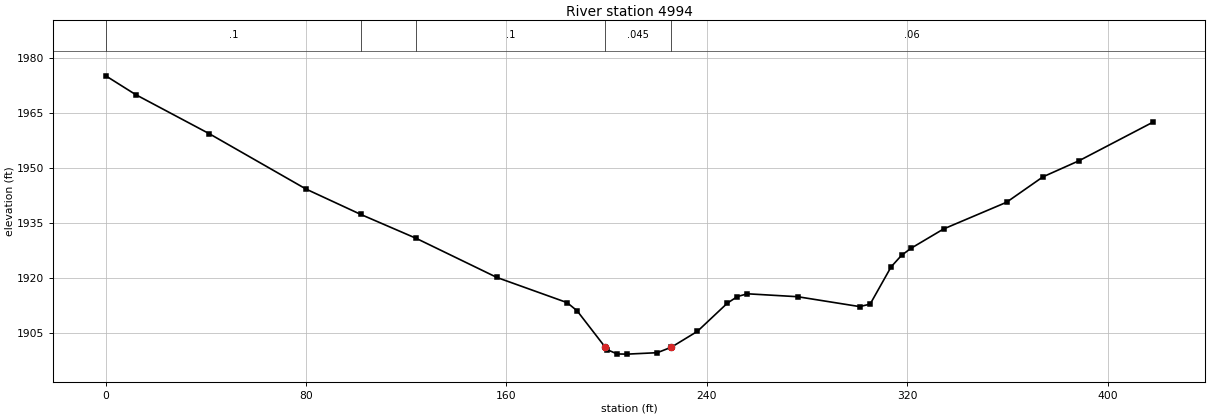
Type RM Length L Ch R = 1 ,4994    ,111.6,108.2,101.3
XS GIS Cut Line= 4
2456250.66454755617143.8926333982456103.59822938617135.353298794
2455966.96887572617140.0973735742455838.87885667617179.947601724
#Sta/Elev= 30
       01975.06111.939581969.94741.386381959.27680.054121944.194  101.811937.324
  123.961930.806156.17251920.159184.18941913.308188.19181911.086  199.42 1901.17
200.19911900.497204.20151899.326208.20391899.281220.21111899.672  225.831901.166
236.22081905.481 248.2281913.181252.2304 1914.97256.23281915.709276.24491914.916
301.01661912.224305.20571912.894313.5839 1923.05 317.7731926.203321.58181928.123
334.52941933.361359.66411940.627374.21931947.558388.6786 1951.96418.17151962.458
#Mann= 5 ,-1 , 0
       0      .1       0  101.81      .1       0  123.96      .1       0
  199.42    .045       0  225.83     .06       0
Bank Sta=199.42,225.83
XS Rating Curve= 0 ,0
Exp/Cntr(USF)=0,0
Exp/Cntr=0.3,0.1