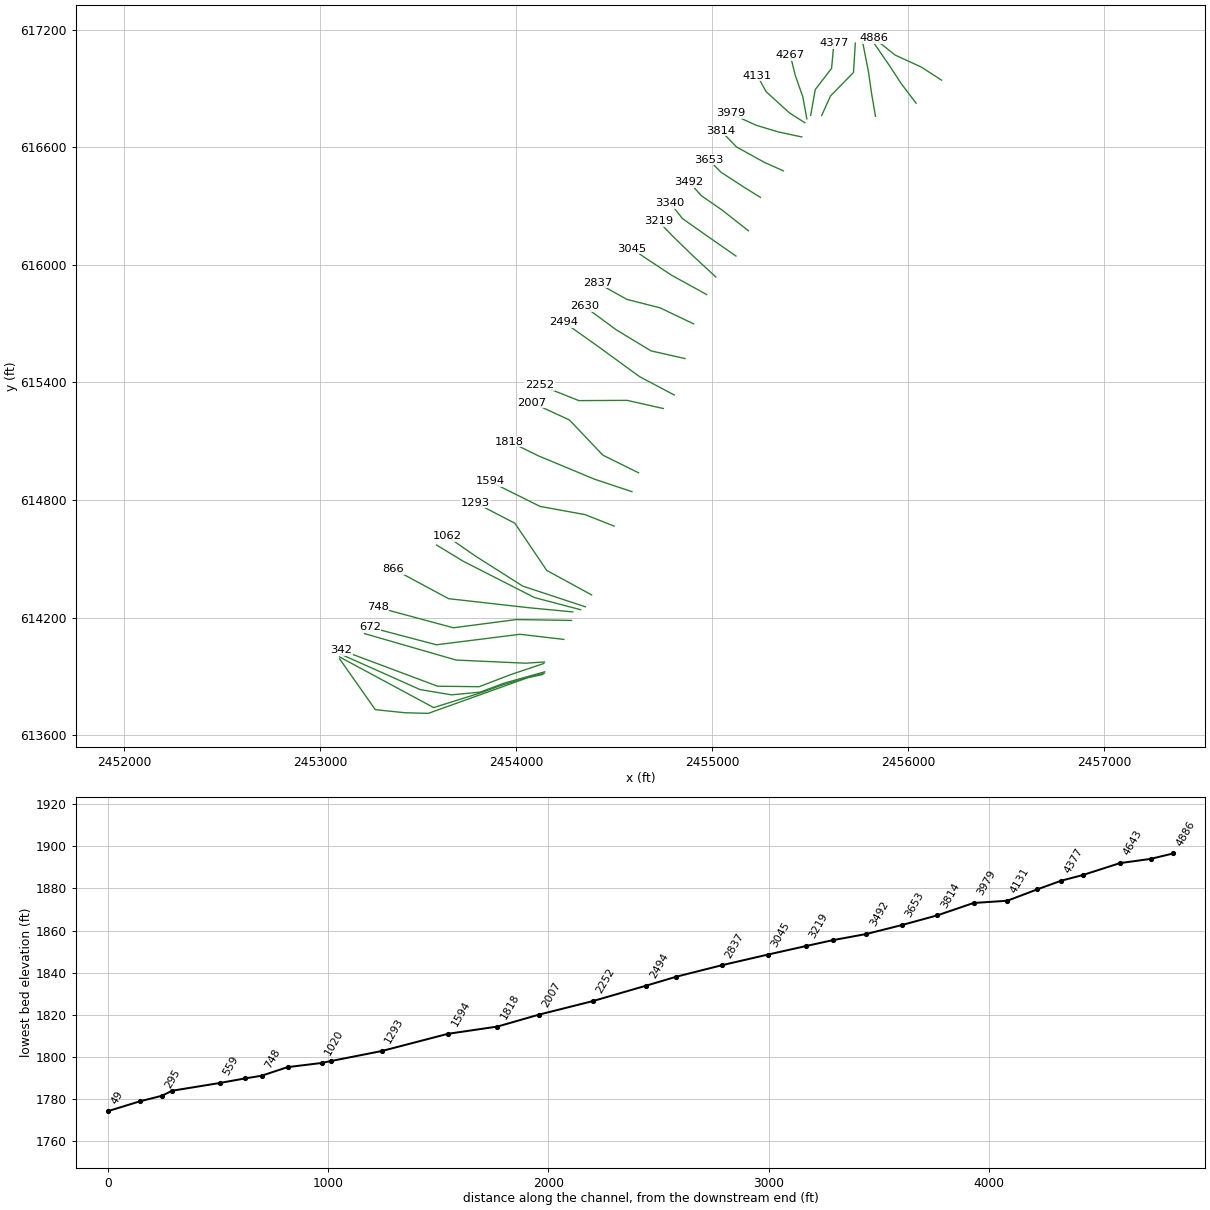
HEC-RAS study DRYRN1.prj: DRYRN1

--- DRYRN1.g01 (geometry) --- (continued)

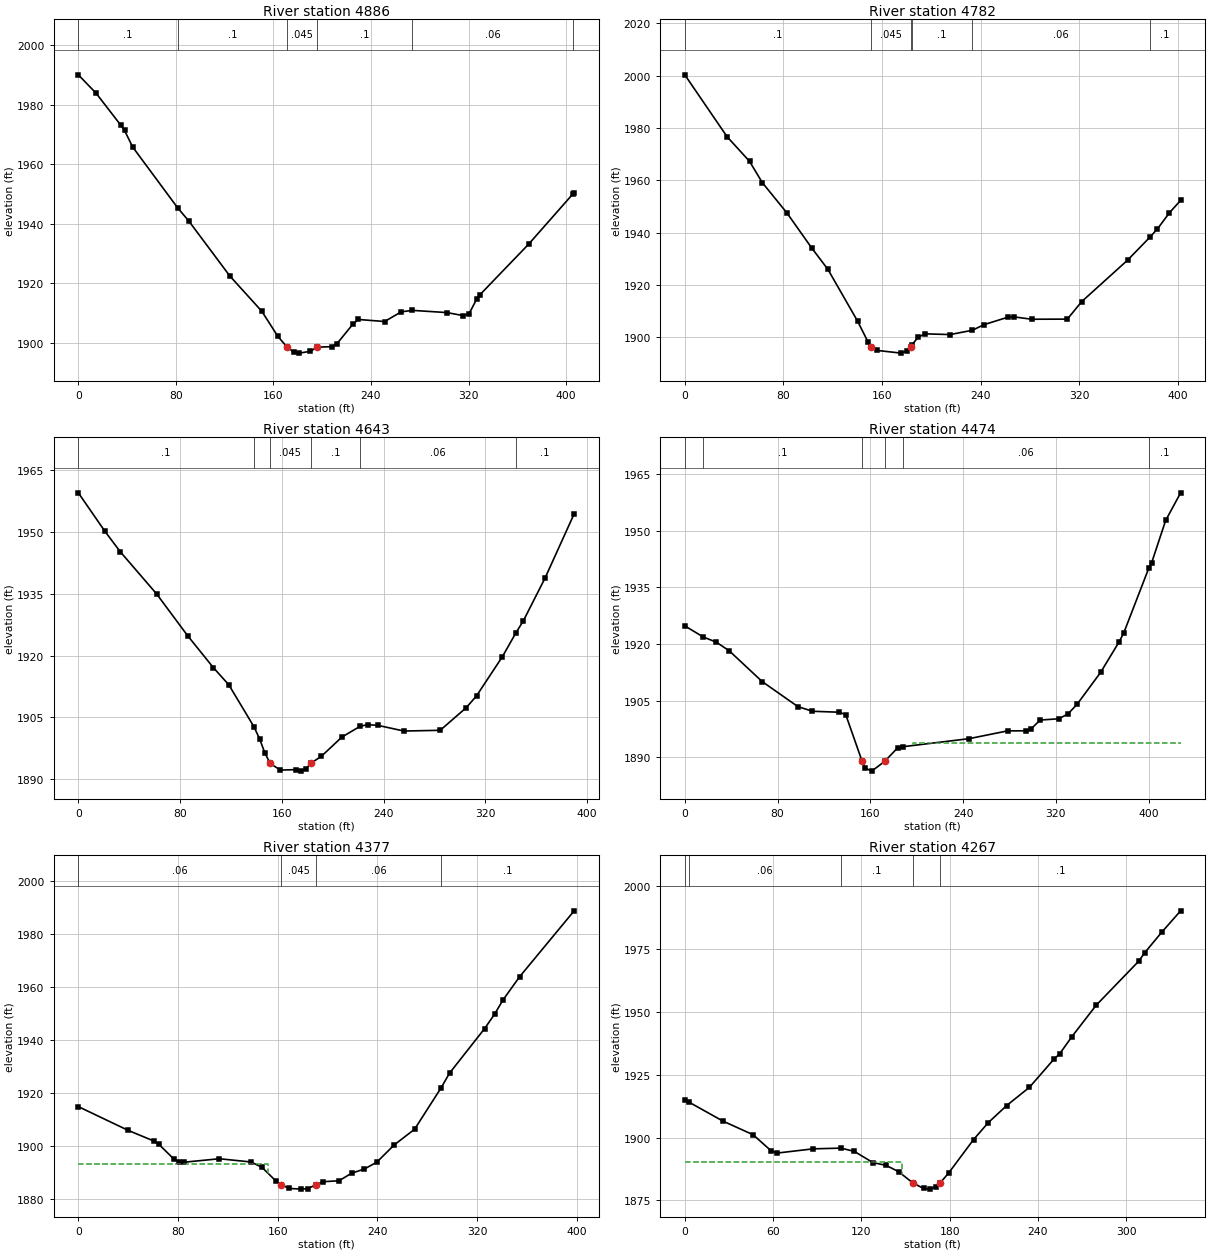
Type RM Length L Ch R = 1 ,4886    ,111.7,103.9,96.5
XS GIS Cut Line= 4
2456170.96409125616942.7438627372456066.59444609617010.109724609
2455933.76035226 617070.83388179 2455827.4930772617156.227227825
#Sta/Elev= 30
       01989.988 14.54331983.82634.984871973.00237.878211971.32944.526971965.784
   81.351945.40790.717061940.865124.22231922.494150.44561910.654  163.641902.211
  171.281898.597176.83451896.875181.23261896.602190.02891897.201   195.91898.597
207.62151898.776212.01961899.733225.21411906.358229.61221907.895251.1734 1907.21
264.7973 1910.46  274.021910.947302.29811910.207315.1979 1909.22320.32931909.745
326.52141914.611329.36651916.205369.19871933.128  405.761950.102406.60411950.436
#Mann= 6 ,-1 , 0
       0      .1       0   81.35      .1       0  171.28    .045       0
   195.9      .1       0  274.02     .06       0  405.76      .1       0
Bank Sta=171.28,195.9
XS Rating Curve= 0 ,0
Exp/Cntr(USF)=0,0
Exp/Cntr=0.3,0.1

Type RM Length L Ch R = 1 ,4782    ,149.2,138.7,135.1
XS GIS Cut Line= 4
2456040.97644228  616825.09080822455968.86650563616919.972303794
2455894.85893907617031.9324685962455810.41440799617154.329597913
#Sta/Elev= 30
       02000.359 34.27771976.71352.501951967.29962.823731959.18282.805951947.581
102.78821934.272 116.0691925.991140.1312 1906.21148.79141898.065  150.931896.469
156.23651895.013175.41611893.997 180.2111894.841  183.24 1896.47  184.091897.038
189.20561900.106194.97911901.364215.18621901.091  233.231902.742242.54471904.857
261.83691907.708266.6965 1907.87281.27541906.948310.22911906.996321.73171913.624
359.02931929.514  377.111938.281383.32741941.502393.04661947.656402.08391952.373
#Mann= 6 ,-1 , 0
       0      .1       0  150.93    .045       0  183.24      .1       0
  184.09      .1       0  233.23     .06       0  377.11      .1       0
Bank Sta=150.93,183.24
XS Rating Curve= 0 ,0
Exp/Cntr(USF)=0,0
Exp/Cntr=0.3,0.1

Type RM Length L Ch R = 1 ,4643    ,175.7,169.3,160.4
XS GIS Cut Line= 4
2455833.47881105616758.2546688062455812.65434014616881.899964849
2455798.33751639616983.4192605472455767.10081002617142.205851254
#Sta/Elev= 30
       01959.42720.926841950.09233.095841945.10361.490181934.94885.828191924.845
106.10991917.083118.27891912.914  138.021902.765142.54571899.773146.58531896.418
  150.791893.884 158.7041892.258170.82281892.355174.8624    1892178.90191892.556
  182.641893.884191.02071895.588 207.1791900.254  221.651902.885227.37691903.253
235.52531903.087255.90861901.713284.44531901.891304.82861907.353312.98191910.225
333.36531919.749  343.911925.484349.67191928.343366.78111938.722389.7404 1954.34
#Mann= 6 ,-1 , 0
       0      .1       0  138.02      .1       0  150.79    .045       0
  182.64      .1       0  221.65     .06       0  343.91      .1       0
Bank Sta=150.79,182.64
XS Rating Curve= 0 ,0
Exp/Cntr(USF)=0,0
Exp/Cntr=0.5,0.3

Type RM Length L Ch R = 1 ,4474    ,96.3,96.7,95.3
XS GIS Cut Line= 4
 2455558.8561009616762.1592571022455604.40963102616862.377023368
 2455721.5472799616982.1177311152455730.65798592617131.793615798
#Sta/Elev= 30
       0 1924.78      161921.82227.166661920.47638.397351918.15266.711171910.034
97.46802 1903.41110.08511902.165133.18671901.915138.78241901.272  152.921888.901
155.56951887.139161.16531886.315  172.371888.905183.54811892.488  187.931892.776
245.10081894.908278.36811896.977294.39771896.992298.40511897.437306.4199 1899.84
322.44951900.177330.46431901.469338.47911904.105358.51611912.445374.5457 1920.57
378.5531 1922.94  400.231940.182402.59761941.532414.61981952.685427.54641960.012
#Mann= 6 ,-1 , 0
       0     .06       0      16      .1       0  152.92    .045       0
  172.37      .1       0  187.93     .06       0  400.23      .1       0
#XS Ineff= 2 , 0
             127  1893.8     197          1893.8
Permanent Ineff=
       F       F
Bank Sta=152.92,172.37
XS Rating Curve= 0 ,0
Exp/Cntr(USF)=0,0
Exp/Cntr=0.5,0.3

Type RM Length L Ch R = 1 ,4377    ,100.3,110.6,124.9
XS GIS Cut Line= 4
2455502.89033532616763.4607865342455526.31786509616894.915259169
2455609.61574874617002.9422020272455621.32951363617130.492086366
#Sta/Elev= 30
       01914.84440.051371905.86360.366511901.89864.429531900.69476.618611895.083
80.681641894.08284.744671893.835113.18231895.156 138.5461893.935147.32651891.962
158.7502 1886.68  163.02 1885.37168.85231883.955178.95441883.678184.00551883.844
  190.991885.368 196.5561886.489209.26081886.832219.36291889.688 229.4651891.243
239.56711893.847253.59511900.384269.93821906.309  291.151921.897298.00451927.503
326.1223 1944.31 334.1561949.777  340.831955.091354.24011963.911398.02481988.806
#Mann= 4 ,-1 , 0
       0     .06       0  163.02    .045       0  190.99     .06       0
  291.15      .1       0
#XS Ineff= 2 , 0
          152.54 1893.28
Permanent Ineff=
       F       F
Bank Sta=163.02,190.99
XS Rating Curve= 0 ,0
Exp/Cntr(USF)=0,0
Exp/Cntr=0.5,0.3

Type RM Length L Ch R = 1 ,4267    ,129.2,135.1,138.5
XS GIS Cut Line= 4
2455483.36739384616745.2393744862455462.54292293616858.472435072
 2455424.7985694616965.1978484982455398.76798076617070.621732493
#Sta/Elev= 30
       01914.994    2.761914.12225.999961906.528 46.41711901.12558.618341894.757
62.685421893.82987.087911895.511  106.061895.803 115.1321894.528127.83881890.041
136.78981888.947145.27531886.439  155.071881.903162.24651879.765166.4892 1879.49
 170.7321880.481  173.431881.906179.2176 1885.84196.18871899.183206.19641905.928
218.73371912.745234.19921920.002250.67971931.094254.79981933.366263.04011940.151
279.52061952.632308.36151970.107312.48161973.505323.94941981.599336.92521990.202
#Mann= 5 ,-1 , 0
       0      .1       0    2.76     .06       0  106.06      .1       0
  155.07    .045       0  173.43      .1       0
#XS Ineff= 2 , 0
          147.87 1890.22
Permanent Ineff=
       F       F
Bank Sta=155.07,173.43
XS Rating Curve= 0 ,0
Exp/Cntr(USF)=0,0
Exp/Cntr=0.3,0.1

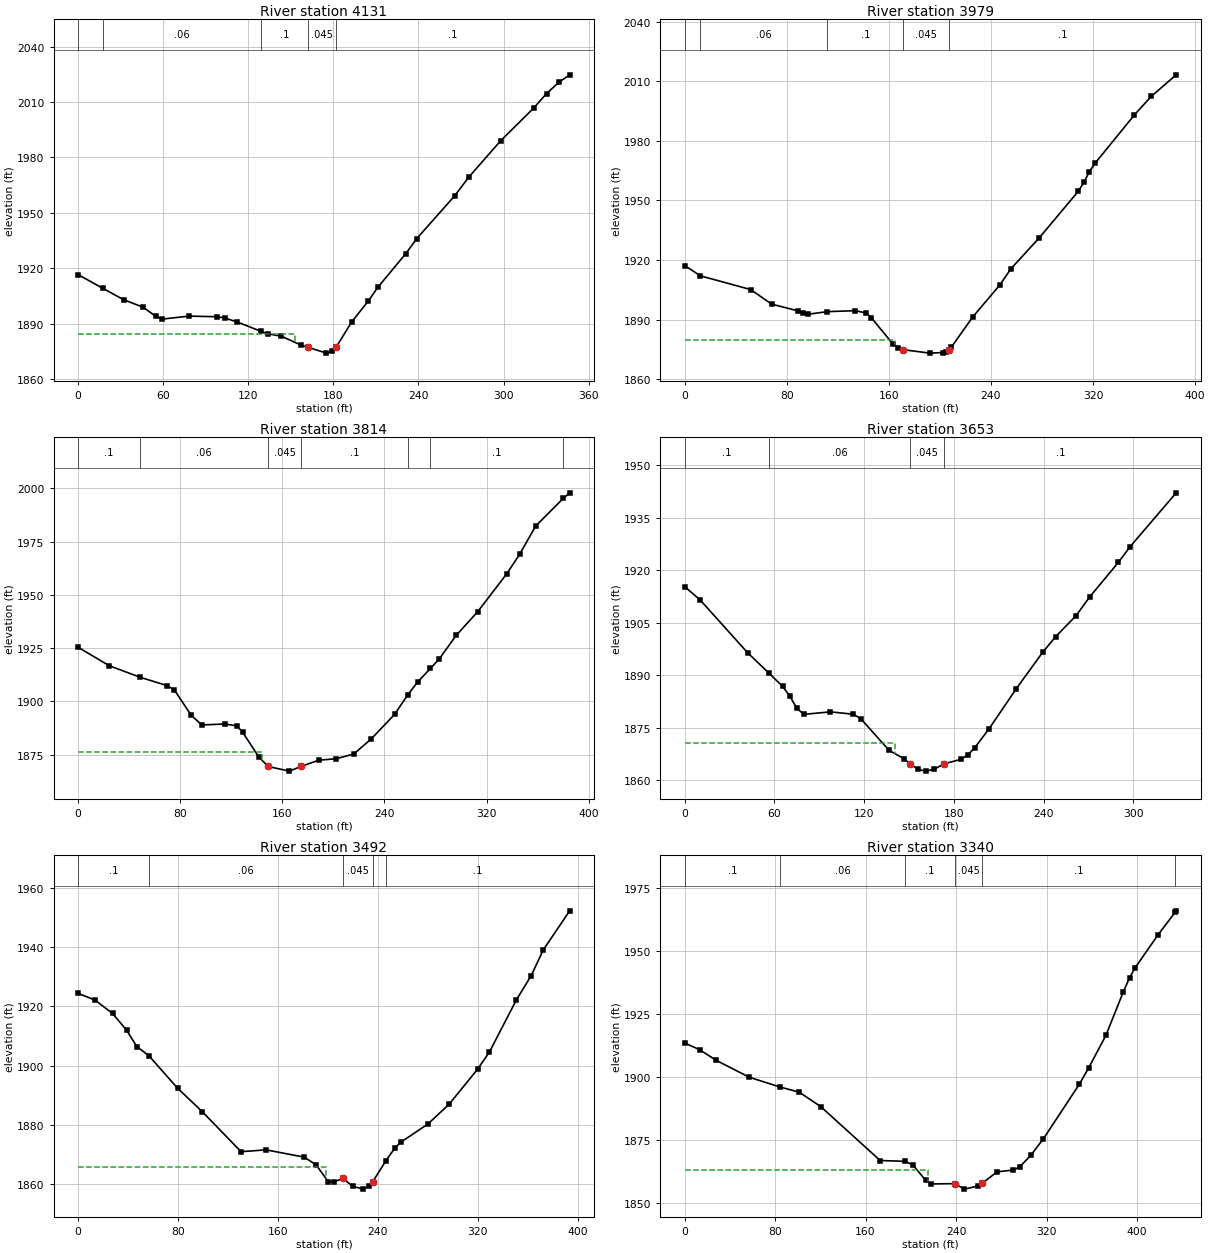
Type RM Length L Ch R = 1 ,4131    ,144.6,152.3,155.8
XS GIS Cut Line= 4
2455472.95515838616725.7164330062455394.86339246616775.174551423
2455275.12268471616884.5030237132455230.87068402616965.197848498
#Sta/Elev= 30
       01916.636   17.561909.11732.09863 1903.0545.935131898.92754.698241894.037
59.432981892.56478.371951894.16898.012841893.812103.42931893.142112.13851890.994
  128.84 1885.96133.54181884.619143.28331883.309157.27121878.427  161.89 1877.34
175.06821874.139179.26021875.071  181.931877.342192.86531890.997  204.731902.431
211.23571909.651231.05511927.969238.84161936.141265.45551959.185275.55091969.405
297.86461988.945321.17072006.659330.27362014.525339.11252020.727346.6117 2024.68
#Mann= 5 ,-1 , 0
       0      .1       0   17.56     .06       0  128.84      .1       0
  161.89    .045       0  181.93      .1       0
#XS Ineff= 2 , 0
          153.16 1884.24
Permanent Ineff=
       F       F
Bank Sta=161.89,181.93
XS Rating Curve= 0 ,0
Exp/Cntr(USF)=0,0
Exp/Cntr=0.3,0.1

Type RM Length L Ch R = 1 ,3979    ,167.5,164.7,162.4
XS GIS Cut Line= 4
 2455457.3368052616652.8307848122455336.29456802616678.861373453
2455224.36303686616712.7011386852455092.90856423616772.571492559
#Sta/Elev= 30
       01917.202   12.421912.00251.748431905.09468.114231897.78288.571491894.422
92.662941893.09296.754391892.674  111.861893.986 133.7861894.473142.14361893.296
146.32241890.926163.0376 1877.83167.21641875.813  171.491874.799192.28931873.095
202.08571873.375204.82571873.749   206.81874.798209.00451876.104225.71971891.266
246.91781907.344255.70851915.598277.68511930.991308.45241954.573312.84771959.063
 317.243  1964.5321.63841968.721352.40571992.991365.5916 2002.35385.19092013.216
#Mann= 5 ,-1 , 0
       0      .1       0   12.42     .06       0  111.86      .1       0
  171.49    .045       0   206.8      .1       0
#XS Ineff= 2 , 0
          164.61 1879.48
Permanent Ineff=
       F       F
Bank Sta=171.49,206.8
XS Rating Curve= 0 ,0
Exp/Cntr(USF)=0,0
Exp/Cntr=0.3,0.1

Type RM Length L Ch R = 1 ,3814    ,163.5,161.7,161.5
XS GIS Cut Line= 4
2455363.62668609616479.7273703532455264.71044926616523.979371042
 2455124.1452706616602.0711369632455043.45044581616685.369020613
#Sta/Elev= 30
       01925.42624.254871916.777   48.551911.32669.668671907.40675.460421905.299
88.606511893.47496.916951888.918114.89171889.364124.33941888.502128.91531885.489
141.36611874.042  148.781869.414165.52191867.221  174.711869.413188.4872 1872.35
202.12861873.049215.85611875.208229.6698 1882.35 247.8871893.829  258.081902.858
266.19031909.238  276.041915.463282.67441919.726296.19341930.963 313.1661942.193
335.79631959.911345.91141969.034358.42661982.314  380.031995.307385.13931997.965
#Mann= 7 ,-1 , 0
       0      .1       0   48.55     .06       0  148.78    .045       0
  174.71      .1       0  258.08      .1       0  276.04      .1       0
  380.03      .1       0
#XS Ineff= 2 , 0
          144.31 1876.27
Permanent Ineff=
       F       F
Bank Sta=148.78,174.71
XS Rating Curve= 0 ,0
Exp/Cntr(USF)=0,0
Exp/Cntr=0.3,0.1

Type RM Length L Ch R = 1 ,3653    ,160.9,161,160.2
XS GIS Cut Line= 4
2455246.48903721616344.3683094222455164.49268299616395.127957271
2455044.75197524616473.2197231932454982.27856251616536.994665362
#Sta/Elev= 30
       01915.32510.36347 1911.5142.038651896.465    56.61890.50165.560721886.783
70.265141884.04374.969551880.58579.673971878.81797.527761879.536112.8491 1878.85
117.76071877.595136.72661868.521 146.6651866.179  150.521864.719155.82861863.165
161.1172  1862.6 166.8981863.148  173.671864.716184.4815 1865.93 189.2571867.175
194.03251869.323203.58341874.709221.81611886.187239.39131896.554247.97541900.978
261.79231907.047270.8397 1912.38290.07811922.274 297.7251926.662328.66711942.112
#Mann= 4 ,-1 , 0
       0      .1       0    56.6     .06       0  150.52    .045       0
  173.67      .1       0
#XS Ineff= 2 , 0
          140.67  1870.7
Permanent Ineff=
       F       F
Bank Sta=150.52,173.67
XS Rating Curve= 0 ,0
Exp/Cntr(USF)=0,0
Exp/Cntr=0.3,0.1

Type RM Length L Ch R = 1 ,3492    ,152.4,152.1,152.1
XS GIS Cut Line= 4
 2455185.3171539616173.8679538262455051.25962241616279.291837821
2454945.83573841616352.1774860142454882.06079624616422.460075343
#Sta/Elev= 30
       01924.37913.449611922.15427.538111917.62138.89317 1911.9446.950611906.464
   56.621903.37979.602871892.42699.411651884.482  130.491870.985150.48391871.609
180.89641869.165190.62221866.538200.34791860.832 205.0091860.862212.04281861.949
219.79951859.355228.12941858.362233.1443 1859.33  235.821860.791  246.52 1867.98
253.83961872.345258.7025  1874.3279.88181880.244297.13261887.022319.8105 1898.79
329.38161904.627350.95981922.219362.83511930.403372.59211939.135393.61561952.233
#Mann= 5 ,-1 , 0
       0      .1       0   56.62     .06       0212.0428    .045       0
  235.82     .06       0  246.52      .1       0
#XS Ineff= 2 , 0
          198.63  1865.9
Permanent Ineff=
       F       F
Bank Sta=212.0428,235.82
XS Rating Curve= 0 ,0
Exp/Cntr(USF)=0,0
Exp/Cntr=0.3,0.1

Type RM Length L Ch R = 1 ,3340    ,122.8,120.8,119
XS GIS Cut Line= 4
2455121.54221173616045.0165400562454971.86632705616149.138894618
2454848.22103101616236.3413665642454785.74761827616315.734661917
#Sta/Elev= 30
       01913.51813.152761910.87227.770771906.67257.006791899.927   84.461896.005
101.34471893.966120.35151888.241   172.91866.814  194.641866.492201.61431865.157
213.09581858.966217.96551857.492 238.9291857.625247.33381855.442259.02161856.644
  263.231857.753276.24381862.322290.59561863.017296.33631864.288306.07051868.865
317.2355 1875.45348.95641897.083357.23651903.575372.50621916.537387.77581933.693
393.46881939.473397.9556 1943.14418.31521956.312  433.731965.482434.65861966.032
#Mann= 6 ,-1 , 0
       0      .1       0   84.46     .06       0  194.64      .1       0
 238.929    .045       0  263.23      .1       0  433.73      .1       0
#XS Ineff= 2 , 0
          215.36 1862.99
Permanent Ineff=
       F       F
Bank Sta=238.929,263.23
XS Rating Curve= 0 ,0
Exp/Cntr(USF)=0,0
Exp/Cntr=0.3,0.1

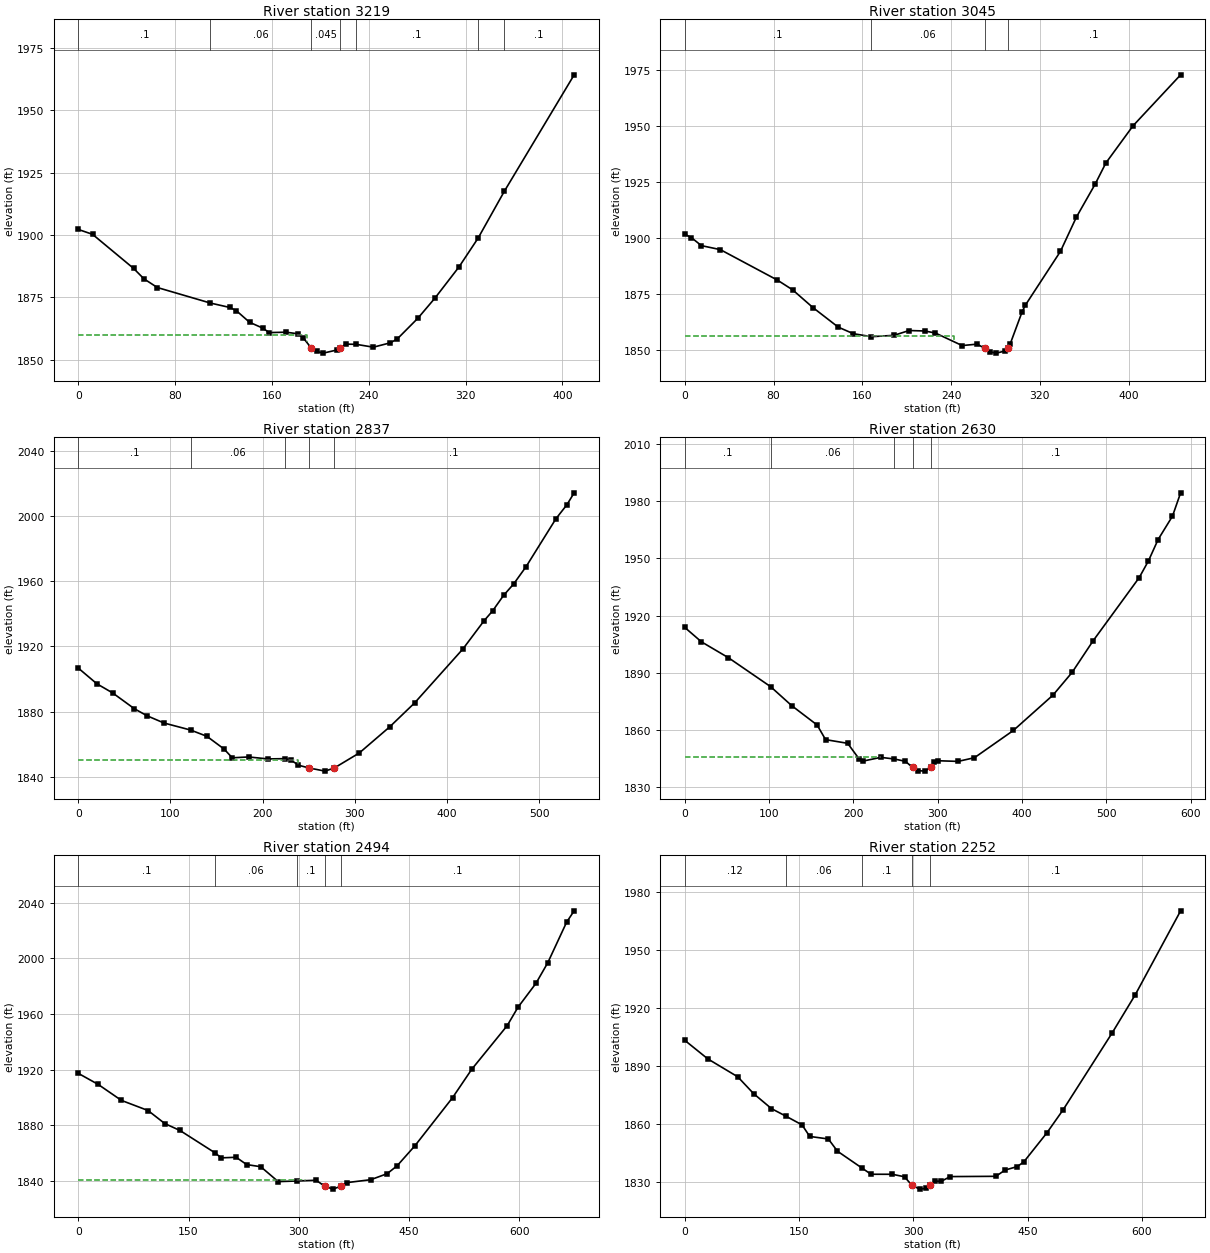
Type RM Length L Ch R = 1 ,3219    ,172.1,174,174.7
XS GIS Cut Line= 4
 2455018.7213866 615938.291126632454901.58373772616046.318069488
2454797.46138316616147.8373651862454724.57573497616223.326072243
#Sta/Elev= 30
       01902.23411.730661900.28745.699561886.60254.19178 1882.46 65.26361878.965
  109.171872.734 125.1181870.977130.55941869.691 141.4421865.048152.32461862.708
157.7659  1860.9171.62591861.065181.55881860.411185.65671858.917  192.261854.835
196.82991853.338202.41651852.672213.58971853.923  216.321854.839221.1599 1856.28
  229.551856.197243.78911855.056257.93241856.824263.58971858.385280.62881866.691
294.70491874.743314.50621887.193  330.371898.795  351.911917.451409.70061964.203
#Mann= 7 ,-1 , 0
       0      .1       0  109.17     .06       0  192.26    .045       0
  216.32     .06       0  229.55      .1       0  330.37      .1       0
  351.91      .1       0
#XS Ineff= 2 , 0
          188.61 1859.89
Permanent Ineff=
       F       F
Bank Sta=192.26,216.32
XS Rating Curve= 0 ,0
Exp/Cntr(USF)=0,0
Exp/Cntr=0.3,0.1

Type RM Length L Ch R = 1 ,3045    ,203.7,208.1,211.2
XS GIS Cut Line= 4
2454971.86632705 615848.485595822454792.25526543615947.401832654
2454650.38855734 616041.11195176 2454591.8197329616082.760893584
#Sta/Elev= 30
       01901.5775.8465671900.11414.979531896.50532.043621894.72583.476771881.142
97.176221876.812115.44211868.925138.27461860.195 151.974 1857.25  168.291855.932
188.50591856.517202.20531858.678216.44541858.462225.89281857.553250.00251851.971
263.50731852.602  270.591850.688275.05491849.152280.82881848.598288.35351849.516
     2911850.686293.14741852.476303.92411866.835 306.8111869.842338.56721893.907
353.00171909.226369.84941923.874379.54131933.329404.08251949.934 446.9381972.628
#Mann= 4 ,-1 , 0
       0      .1       0  168.29     .06       0  270.59    .045       0
     291      .1       0
#XS Ineff= 2 , 0
           242.8 1856.27
Permanent Ineff=
       F       F
Bank Sta=270.59,291
XS Rating Curve= 0 ,0
Exp/Cntr(USF)=0,0
Exp/Cntr=0.3,0.1

Type RM Length L Ch R = 1 ,2837    ,209.6,206.5,203.5
XS GIS Cut Line= 4
2454905.48832602615698.8097111372454733.68644099615780.806065354
2454564.48761483615823.7565366112454413.51020071615908.355949693
#Sta/Elev= 30
       01906.68420.120191897.08337.334711891.44960.658661881.85574.480981877.499
93.05412 1873.03  121.831868.736 139.4871864.909158.13291857.104167.03211851.727
 184.761 1852.25205.78151851.045  224.041851.208230.54271850.442238.79641847.188
  250.491845.489267.68441843.566  277.731845.488304.82621854.674337.84111870.683
364.93131885.394417.36571918.475440.2915 1935.75449.46191941.715461.35361951.202
472.38771958.285485.90191968.921518.23941998.233 530.1352006.809537.99562014.102
#Mann= 5 ,-1 , 0
       0      .1       0  121.83     .06       0  224.04      .1       0
  250.49    .045       0  277.73      .1       0
#XS Ineff= 2 , 0
          238.68 1850.63
Permanent Ineff=
       F       F
Bank Sta=250.49,277.73
XS Rating Curve= 0 ,0
Exp/Cntr(USF)=0,0
Exp/Cntr=0.3,0.1

Type RM Length L Ch R = 1 ,2630    ,137,136.4,135.4
XS GIS Cut Line= 4
2454861.23632533615521.8017083812454688.13291087615560.847591342
2454509.82337868  615668.87453422454347.13219968615788.615241947
#Sta/Elev= 30
       01913.70819.723891906.14951.75983 1897.78  101.771882.559126.78961872.564
156.9018 1862.39166.93921854.694193.10561852.756207.1361 1844.27211.81291843.434
232.3736 1845.37  248.611844.496261.49741843.283   270.11840.092276.05941838.388
284.79651838.123  291.521840.096295.99571842.675300.67251843.582324.05661843.244
343.50681845.193389.5768 1859.51436.5713 1878.11459.28761890.083484.12061906.667
538.75321939.887549.78981948.746561.23361959.969578.28141972.275587.93851984.542
#Mann= 5 ,-1 , 0
       0      .1       0  101.77     .06       0  248.61      .1       0
   270.1    .045       0  291.52      .1       0
#XS Ineff= 2 , 0
          232.84 1845.46
Permanent Ineff=
       F       F
Bank Sta=270.1,291.52
XS Rating Curve= 0 ,0
Exp/Cntr(USF)=0,0
Exp/Cntr=0.3,0.1

Type RM Length L Ch R = 1 ,2494    ,234,242.3,248.2
XS GIS Cut Line= 4
2454806.57208918615335.6829996012454629.56408643615429.393118707
2454409.60561242615589.4812388472454244.31137455615706.618887729
#Sta/Elev= 30
       01917.25426.960141909.32658.641951897.79594.84973 1890.51117.65761881.119
138.37261876.125  186.561859.854194.4211 1856.41214.82671856.826229.14321851.564
248.29531850.025272.09281839.294  297.021839.744323.63241840.277  335.43    1836
346.53881833.886  357.62    1836365.96731838.607398.07841840.682420.34691845.003
433.94181850.697458.20791865.146509.35941899.724535.64831920.297583.69371951.581
598.40141964.826622.91421982.106638.94121996.875664.76442026.266674.92282034.332
#Mann= 5 ,-1 , 0
       0      .1       0  186.56     .06       0  297.02      .1       0
  335.43    .045       0  357.62      .1       0
#XS Ineff= 2 , 0
          308.31 1840.33
Permanent Ineff=
       F       F
Bank Sta=335.43,357.62
XS Rating Curve= 0 ,0
Exp/Cntr(USF)=0,0
Exp/Cntr=0.3,0.1

Type RM Length L Ch R = 1 ,2252    ,255,244.6,233
XS GIS Cut Line= 4
2454750.60632361615266.7019397042454565.78914426615308.350881529
2454319.80008161615307.0493520972454119.36454908 615386.44264745
#Sta/Elev= 30
       01903.52130.158081893.94569.563061884.65290.390211875.945113.81381868.199
  132.771864.302153.96861859.796164.0073 1853.82 188.4721852.504200.49621846.167
  232.791837.425244.49681834.259272.49721834.242288.4974 1832.95  298.271828.495
308.49771826.564316.4978 1826.95  321.941828.496 328.4981830.753336.49811830.558
348.49821833.051408.49911833.194420.49921836.427436.57921838.224445.18391840.678
475.30051855.602496.81231867.636561.34791907.501591.46451927.102651.03131970.518
#Mann= 5 ,-1 , 0
       0     .12       0  132.77     .06       0  232.79      .1       0
  298.27    .045       0  321.94      .1       0
Bank Sta=298.27,321.94
XS Rating Curve= 0 ,0
Exp/Cntr(USF)=0,0
Exp/Cntr=0.3,0.1

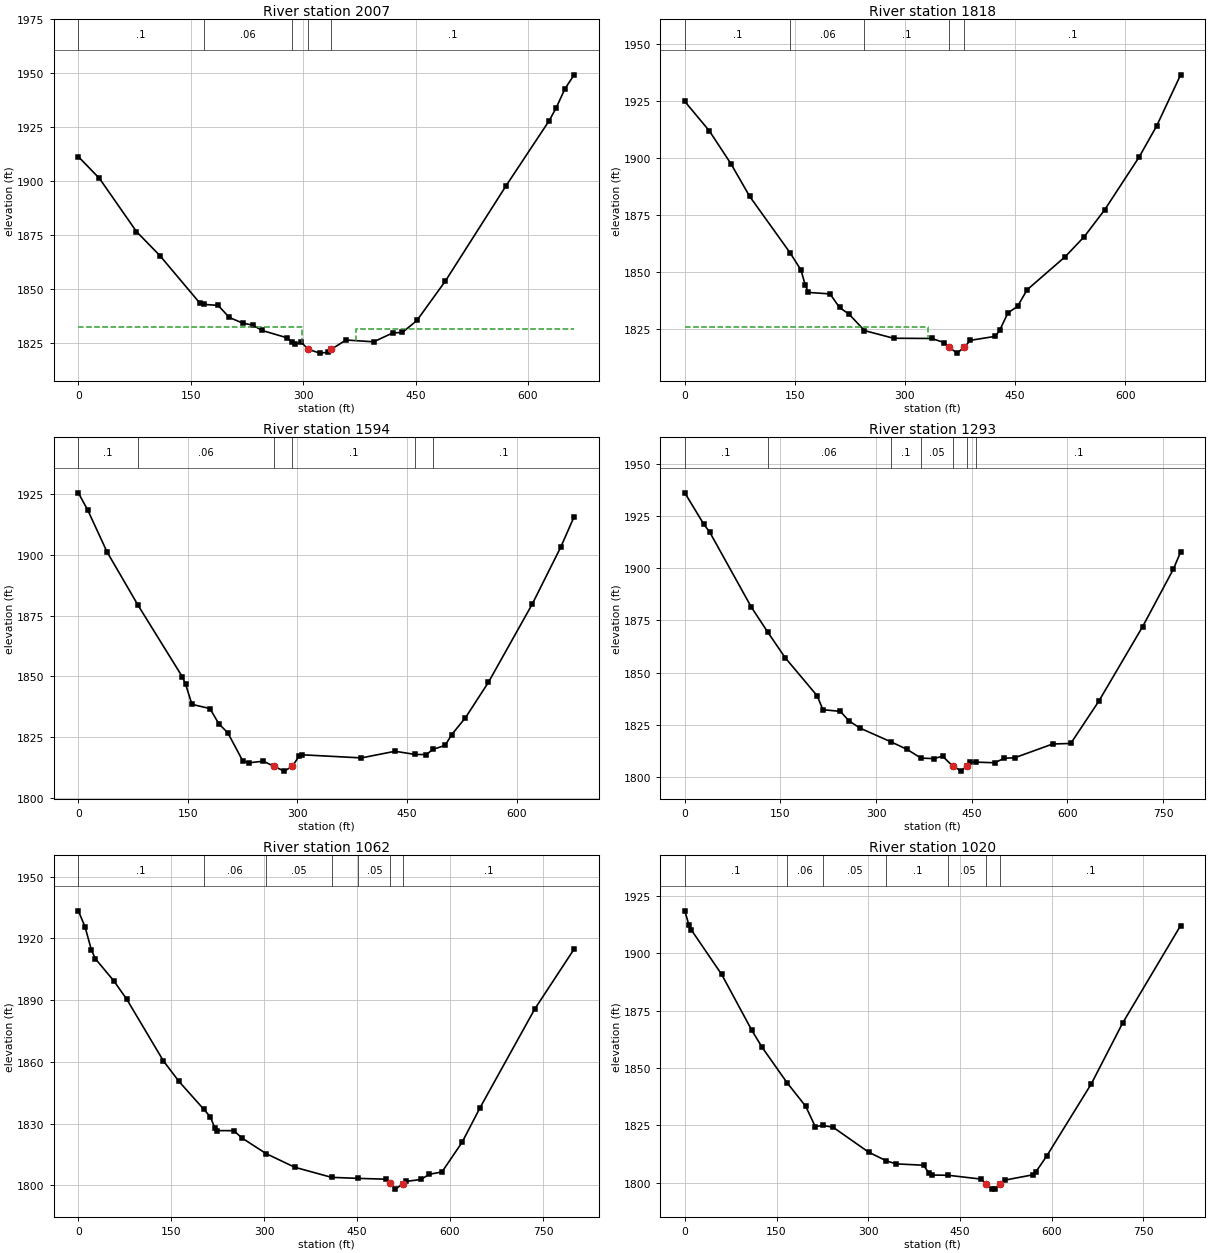
Type RM Length L Ch R = 1 ,2007    ,183.9,188.5,193.8
XS GIS Cut Line= 4
 2454624.3579687614938.7165228332454442.14384822615028.522053643
2454271.64349262615208.1331152632454080.31866611615296.637116641
#Sta/Elev= 30
       01911.27128.219341901.15177.608531876.498108.87321865.336162.33771843.254
  167.031842.733186.53981842.273201.47571836.661219.69951833.998 232.6871833.141
245.01581830.656277.79911827.306  284.571825.501289.13781824.276297.76291825.094
  306.661821.908322.22921820.127333.25981820.517  337.521821.906  357.181826.214
393.99821825.377419.42641829.478432.53421829.757451.7827 1835.27 489.7071853.536
570.77821897.775628.07231927.838637.3598 1933.73649.4131 1942.81661.59641949.218
#Mann= 5 ,-1 , 0
       0      .1       0  167.03     .06       0  284.57      .1       0
  306.66    .045       0  337.52      .1       0
#XS Ineff= 2 , 0
          298.25 1832.38  370.32         1831.11
Permanent Ineff=
       F       F
Bank Sta=306.66,337.52
XS Rating Curve= 0 ,0
Exp/Cntr(USF)=0,0
Exp/Cntr=0.3,0.1

Type RM Length L Ch R = 1 ,1818    ,223.2,224.6,227.1
XS GIS Cut Line= 4
2454590.51820347614842.4033448632454399.19337696614906.178287033
2454114.15843135615024.617465347 2453965.7840761615097.503113541
#Sta/Elev= 30
       01924.69733.491861911.78163.006451897.32988.304661883.173  143.581858.355
  158.321850.842164.19931844.201168.4157 1841.06197.93031840.403210.82271834.457
223.81751831.543  244.821824.351284.45961820.985336.43851820.891353.76491819.057
  359.591817.167371.09121814.473  381.091817.169389.22531820.079423.07011821.825
 429.0061824.429440.39641832.141453.39121834.908466.38591842.198518.5965 1856.77
544.47081865.536572.07511877.193619.18371900.386643.09181914.029675.64651936.355
#Mann= 5 ,-1 , 0
       0      .1       0  143.58     .06       0  244.82      .1       0
  359.59    .045       0  381.09      .1       0
#XS Ineff= 2 , 0
          331.22 1826.03
Permanent Ineff=
       F       F
Bank Sta=359.59,381.09
XS Rating Curve= 0 ,0
Exp/Cntr(USF)=0,0
Exp/Cntr=0.3,0.1

Type RM Length L Ch R = 1 ,1594    ,309.9,301,291.5
XS GIS Cut Line= 4
2454499.41114323 614666.696871542454351.03678798614725.265695981
2454121.96760794614766.9146378062453865.56630983614894.464522145
#Sta/Elev= 30
       01925.48612.996091918.30739.419341901.113    81.81879.223142.49371849.758
146.92831846.679 155.5291838.488180.14011836.761192.33691830.495204.53361826.818
224.86151815.367232.99261814.434253.32051815.105  267.941812.984281.77961811.029
  292.961812.984302.10751817.182 306.1731817.752387.48461816.467433.51111819.193
  460.811817.904476.3565 1817.82  485.071819.928502.13051821.632511.08081826.044
529.96781833.018 561.2411847.504621.46851879.794660.25341903.089678.71531915.702
#Mann= 6 ,-1 , 0
       0      .1       0    81.8     .06       0  267.94    .045       0
  292.96      .1       0  460.81     .05       0  485.07      .1       0
#XS Ineff= 2 , 0
                          313.79         1817.59
Permanent Ineff=
       F       F
Bank Sta=267.94,292.96
XS Rating Curve= 0 ,0
Exp/Cntr(USF)=0,0
Exp/Cntr=0.3,0.1

Type RM Length L Ch R = 1 ,1293    ,226.7,230.5,235.5
XS GIS Cut Line= 4
2454384.87655321614315.2839248932454155.80737317614440.230750367
2453993.11619417614681.0136952922453792.68066164614785.136049854
#Sta/Elev= 30
       01936.12629.766081921.08438.878781917.398104.46931881.313  129.781869.546
157.34391857.178207.46381838.943216.57651832.269243.91461831.463257.5836 1826.86
275.13461823.396  323.361816.854348.56351813.254  370.281809.086390.37131808.838
404.13731809.993  419.991805.302433.58511802.848  441.691805.299447.58471807.013
  456.441807.155486.20461806.854 500.6871809.018517.1317 1809.24576.73351815.837
605.10481816.105648.85381836.208717.83141872.061766.04941899.592777.3907 1907.82
#Mann= 7 ,-1 , 0
       0      .1       0  129.78     .06       0  323.36      .1       0
  370.28     .05       0  419.99    .045       0  441.69     .05       0
  456.44      .1       0
Bank Sta=419.99,441.69
XS Rating Curve= 0 ,0
Exp/Cntr(USF)=0,0
Exp/Cntr=0.5,0.3

Type RM Length L Ch R = 1 ,1062    ,40.8,41.7,42.8
XS GIS Cut Line= 4
2454353.06138931614254.5458847322454033.46360656614360.114383107
2453791.95758973614513.4056273232453645.89706458614614.635694259
#Sta/Elev= 30
       01933.45510.864591925.61521.10639 1914.4227.439581910.15557.202861899.419
78.265711890.398137.24171860.504162.51711850.454  202.581836.917213.06791833.245
220.60171827.596223.76831826.561250.98111826.544263.61881823.078  303.151815.366
349.27741808.749  408.721803.835     4521803.329497.06481802.935  503.631800.845
511.55571798.106  524.821800.842529.31131801.871     5531802.791 566.6211805.338
586.90831806.436619.3283 1820.83 648.4391837.703736.67521885.673800.34091914.882
#Mann= 7 ,-1 , 0
       0      .1       0  202.58     .06       0  303.15     .05       0
  408.72      .1       0     452     .05       0  503.63    .045       0
  524.82      .1       0
#XS Ineff= 2 , 0
             483  1800.9     544          1800.9
Permanent Ineff=
       F       F
Bank Sta=503.63,524.82
XS Rating Curve= 0 ,0
Exp/Cntr(USF)=0,0
Exp/Cntr=0.5,0.3

Type RM Length L Ch R = 1 ,1020    ,148.6,154.8,157.6
XS GIS Cut Line= 4
2454329.09504656614239.664006385 2454094.3437001614301.293238153
2453729.05043544614487.301464944 2453593.8119686614569.605194327
#Sta/Elev= 30
       0 1918.61     6.6 1912.52    10.7 1910.27    60.3 1890.86   109.4 1866.59
   126.5 1859.04     167 1843.71   197.8 1833.31   213.3  1824.5   225.7 1824.97
   242.3 1824.24   300.6 1813.33   329.8 1809.52   345.5 1808.22   390.4 1807.62
   399.4 1804.18   404.2 1803.35     431 1803.24   484.5 1801.58   493.1  1799.5
   502.6  1797.2   507.1 1797.35   515.61799.552   523.2 1801.12   569.9 1803.48
   574.4 1804.83   591.6 1811.51   664.7 1843.07   716.2 1869.72   810.9 1912.18
#Mann= 7 ,-1 , 0
       0      .1       0     167     .06       0   225.7     .05       0
   329.8      .1       0     431     .05       0   493.1    .045       0
   515.6      .1       0
Bank Sta=493.1,515.6
XS Rating Curve= 0 ,0
Exp/Cntr(USF)=0,0
Exp/Cntr=0.5,0.3

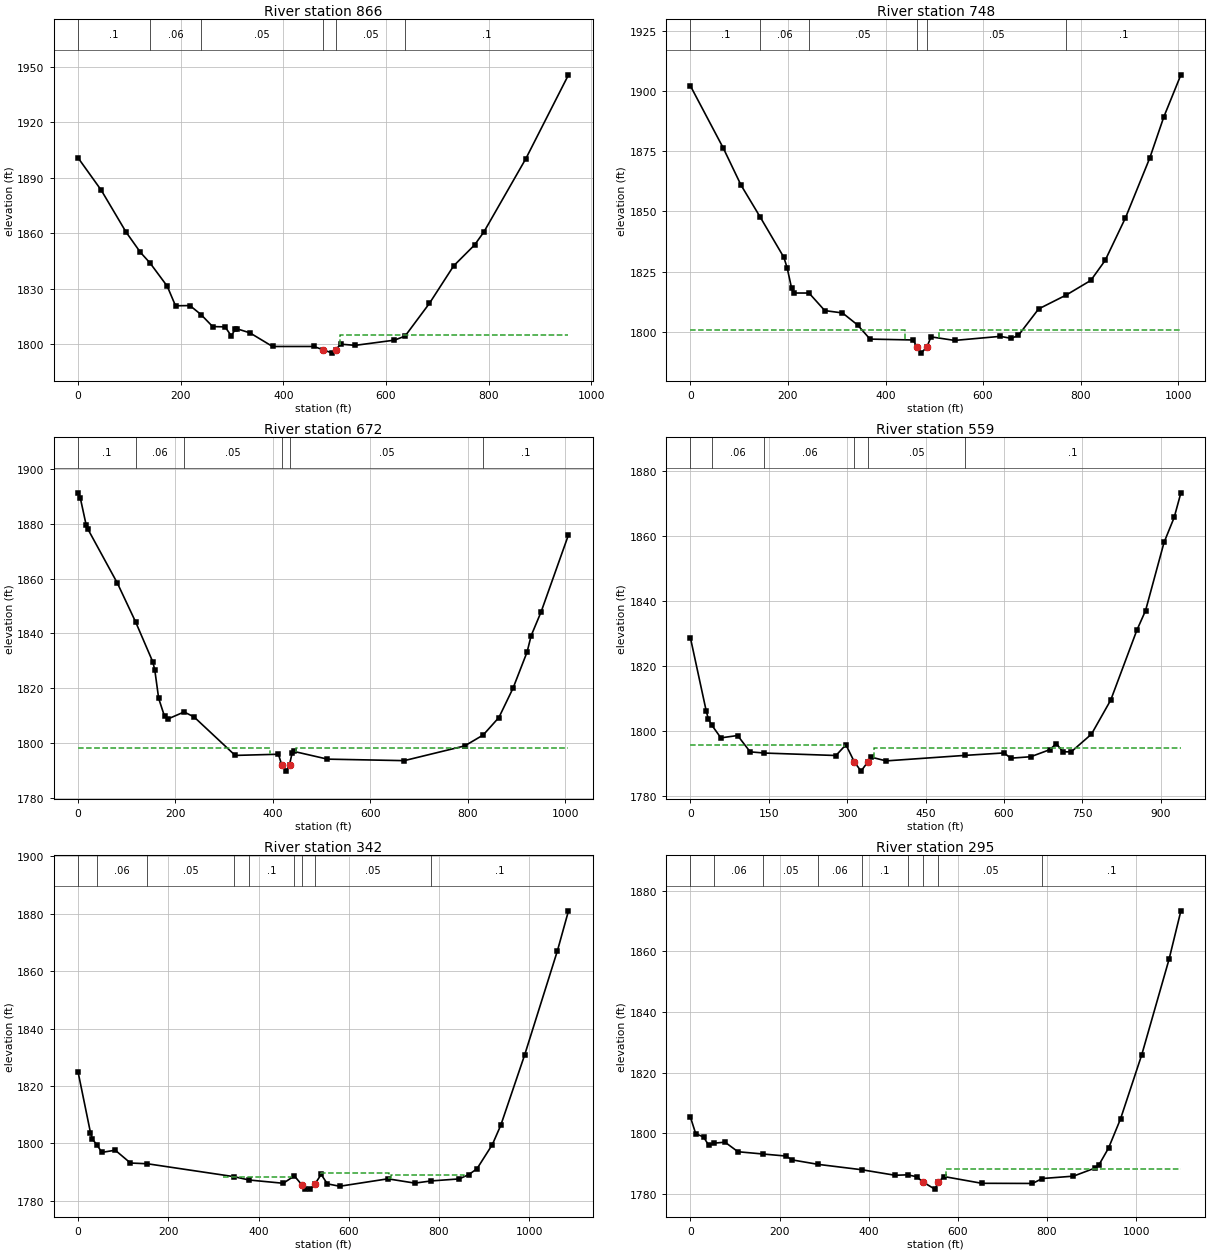
Type RM Length L Ch R = 1 ,866     ,113.2,118,119.5
XS GIS Cut Line= 4
2454287.82262824614228.6309875962454067.68740332614249.519731567
2453654.73300328614296.117698886 2453373.5383729 614447.15938606
#Sta/Elev= 30
       01900.87245.280081883.326 93.49571860.736121.62151849.707   140.11844.045
173.85511831.407189.92691820.835218.05271820.948  239.621816.084262.3263 1809.58
286.47861809.424298.55471804.613306.41221808.062310.63091808.302334.78321806.212
379.0624 1798.81459.57021798.823  476.651797.119495.79861795.219   502.51797.118
511.90021800.068540.07791799.425616.56021802.234  637.391804.437684.8253 1822.14
732.03661842.424772.9013 1853.76791.06341860.824872.7928 1900.45 955.8921945.787
#Mann= 6 ,-1 , 0
       0      .1       0   140.1     .06       0  239.62     .05       0
  476.65    .045       0   502.5     .05       0  637.39      .1       0
#XS Ineff= 2 , 0
                          510.71         1804.95
Permanent Ineff=
       F       F
Bank Sta=476.65,502.5
XS Rating Curve= 0 ,0
Exp/Cntr(USF)=0,0
Exp/Cntr=0.5,0.3

Type RM Length L Ch R = 1 ,748     ,76.1,76.1,76.1
XS GIS Cut Line= 4
2454282.20034246 614185.130981692454000.20229885 614189.46941313
2453679.15837229614147.5312425432453293.03797412614251.653597105
#Sta/Elev= 30
       01901.99667.463291876.161103.63331860.867  142.71  1847.7 191.4781830.898
198.18991826.623207.4799 1818.01211.48031816.078  243.091816.074275.48791808.781
 311.7391807.812342.71771802.824368.2147 1796.96456.96241796.591  463.681793.817
473.09831791.137  485.221793.822493.26821797.889 541.6761796.412635.23131798.094
657.82541797.267672.51721798.517 713.9461809.474  770.89 1815.28820.97441821.312
850.3412 1829.59892.09011847.293941.80471872.061970.80491889.2131005.7161906.618
#Mann= 6 ,-1 , 0
       0      .1       0  142.71     .06       0  243.09     .05       0
  463.68    .045       0  485.22     .05       0  770.89      .1       0
#XS Ineff= 2 , 0
             440 1800.91  510.67         1800.91
Permanent Ineff=
       F       F
Bank Sta=463.68,485.22
XS Rating Curve= 0 ,0
Exp/Cntr(USF)=0,0
Exp/Cntr=0.5,0.3

Type RM Length L Ch R = 1 ,672     ,114.9,113.2,111.9
XS GIS Cut Line= 4
 2454243.1544595614088.2393461952454019.00216843614114.269934835
2453592.38974349614060.7626137412453252.54594735614150.423530169
#Sta/Elev= 30
       01891.2224.4390531889.488 16.51971879.58420.546581877.88280.949811858.243
  118.291844.156153.4337 1829.65157.46061826.803165.51431816.346 177.5951809.787
185.64871808.935  217.711811.391238.01181809.608  322.671795.567411.35941795.996
  418.081792.218427.48481789.844   434.21792.218439.57881796.453443.61021797.006
512.14291794.212669.72521793.663793.8313 1799.03  831.861802.995864.15811809.376
893.11611820.026922.07431833.248 930.3481839.166951.03231847.9481007.0861875.928
#Mann= 6 ,-1 , 0
       0      .1       0  118.29     .06       0  217.71     .05       0
  418.08    .045       0   434.2     .05       0  831.86      .1       0
#XS Ineff= 2 , 0
          393.33 1798.12  446.67         1798.12
Permanent Ineff=
       F       F
Bank Sta=418.08,434.2
XS Rating Curve= 0 ,0
Exp/Cntr(USF)=0,0
Exp/Cntr=0.5,0.3

Type RM Length L Ch R = 1 ,559     ,214.2,216.3,215.1
XS GIS Cut Line= 4
2454144.81507336613973.1455805692454048.40548581613966.718274731
 2453693.2968383613982.7865393242453225.71033865614117.759961905
#Sta/Elev= 30
       01828.61230.136781806.21334.145661803.748   40.571801.89158.198941797.924
90.269971798.641114.30211793.623  141.621793.254278.46991792.502297.57841795.806
  313.751790.521 326.5191787.701  339.47 1790.52346.5395 1791.97374.56811790.846
 525.5281792.539600.46761793.296612.95751791.676651.31561792.123687.89721794.299
700.38711796.178712.87711793.627728.85311793.632767.62191799.069  804.471809.538
854.42981830.983871.0831 1837.01906.54351857.995925.92791865.661938.77311873.219
#Mann= 6 ,-1 , 0
       0      .1       0   40.57     .06       0  141.62     .06       0
  313.75    .045       0  339.47     .05       0 525.528      .1       0
#XS Ineff= 2 , 0
          293.51 1795.66  351.11         1794.77
Permanent Ineff=
       F       F
Bank Sta=313.75,339.47
XS Rating Curve= 0 ,0
Exp/Cntr(USF)=0,0
Exp/Cntr=0.5,0.3

Type RM Length L Ch R = 1 ,342     ,45.9,47,44.8
XS GIS Cut Line= 5
2454140.86708766613965.2393883262453973.73790409613909.191324329
2453810.76575657613846.7598155032453598.53449252613849.257645857
2453107.74164436614033.087714754
#Sta/Elev= 30
       01824.86527.55182 1803.6831.770761801.461   41.681799.46852.865451796.834
82.39802  1797.6116.14951793.127  153.911792.865  345.931788.371  379.071787.212
454.82591786.071   479.51788.646  495.781785.555502.82931784.102514.83011784.031
  524.55 1785.69538.83171789.151 552.5891785.876579.90471785.029686.68911787.623
746.48851786.128  782.651786.885844.73021787.591866.08721789.093884.21751791.117
918.39951799.579937.04431806.297989.95721830.8031062.5711867.0881087.1351881.011
#Mann= 9 ,-1 , 0
       0      .1       0   41.68     .06       0  153.91     .05       0
  345.93     .06       0  379.07      .1       0   479.5     .05       0
  495.78    .045       0  524.55     .05       0  782.65      .1       0
#XS Ineff= 3 ,-1
  320.52  474.36 1788.42  538.86  689.031789.573  693.53  855.551788.841
Permanent Ineff=
       F       F       F
Bank Sta=495.78,524.55
XS Rating Curve= 0 ,0
Exp/Cntr(USF)=0,0
Exp/Cntr=0.5,0.3

Type RM Length L Ch R = 1 ,295     ,114.7,99.9,99.2
XS GIS Cut Line= 6
2454145.40414763613922.8201023562453937.12977665613864.411053668
2453815.70043859613819.0671869232453670.44635698613805.233464865
2453509.05293297613832.132368866 2453102.4952125614013.507835846
#Sta/Elev= 30
       01805.33911.83274 1799.8829.364771798.836 41.03271796.047   53.081796.777
77.539441797.109106.61971793.955  162.561793.206 214.632 1792.53227.39471791.283
  286.621789.786  384.441788.016459.39531786.188  487.091786.339507.75811785.711
  520.761784.066548.30981781.623556.4202 1783.93568.58571785.783653.74441783.546
767.48711783.496  789.671785.122859.4672  1785.9907.64721788.561 916.7431789.614
938.30731795.177965.20361804.7931012.7671825.9261074.0871857.4321100.6411873.401
#Mann= 9 ,-1 , 0
       0      .1       0   53.08     .06       0  162.56     .05       0
  286.62     .06       0  384.44      .1       0  487.09     .05       0
  520.76    .045       0556.4202     .05       0  789.67      .1       0
#XS Ineff= 2 , 0
                          573.33         1788.22
Permanent Ineff=
       F       F
Bank Sta=520.76,556.4202
XS Rating Curve= 0 ,0
Exp/Cntr(USF)=0,0
Exp/Cntr=0.5,0.3

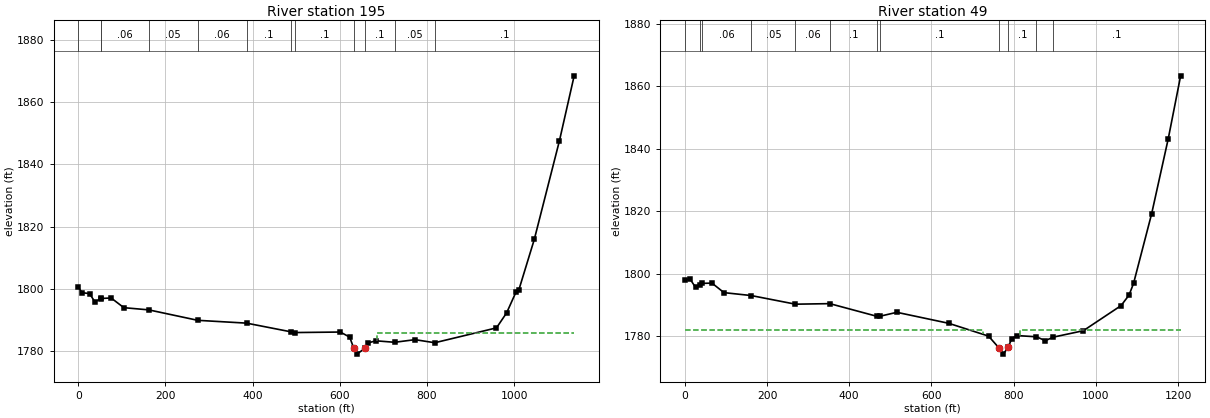
Type RM Length L Ch R = 1 ,195     ,131.9,145.8,153.9
XS GIS Cut Line= 6
2454143.77330551613916.1151278372454077.71797437613899.979474429
2453921.40383197613853.0852317112453824.08567236613817.284250712
2453578.52119705613740.1356578542453097.98126899613998.810351553
#Sta/Elev= 30
       01800.5038.4820271798.74525.764171798.462  38.1171795.761   51.331796.858
   51.711796.884 75.27751797.047104.51041793.928  161.741793.221  274.081789.861
  386.161788.956  488.591786.146  497.28 1785.93601.16911786.094622.81941784.465
  632.09 1780.92639.37351778.991  658.351780.919664.80371782.563682.46721783.284
  726.031782.798772.75861783.644  818.141782.654959.73271787.434983.03191792.258
1004.4911798.9371010.7261799.4851046.5011815.8641104.2131847.5841138.0371868.485
#Mann= 12 ,-1 , 0
       0      .1       0   51.33    .035       0   51.71     .06       0
  161.74     .05       0  274.08     .06       0  386.16      .1       0
  488.59     .06       0  497.28      .1       0  632.09    .045       0
  658.35      .1       0  726.03     .05       0  818.14      .1       0
#XS Ineff= 2 , 0
                          685.78         1785.89
Permanent Ineff=
       F       F
Bank Sta=632.09,658.35
XS Rating Curve= 0 ,0
Exp/Cntr(USF)=0,0
Exp/Cntr=0.3,0.1

Type RM Length L Ch R = 1 ,49      ,49,49,49
XS GIS Cut Line= 6
2454135.40103482613909.2269925782454057.09326166613892.255345924
 2453551.2190921 613710.628951912453431.22657278613713.904181966
 2453280.5282455613729.704818506 2453098.6313024 613988.65312596
#Sta/Elev= 30
       01798.105   12.951798.277  26.0631795.661  37.5071796.375  42.8821796.936
  66.1571797.005   95.341793.964 161.4271793.034 269.2411790.271 352.6991790.445
 468.1251786.366 474.3611786.406 515.899 1787.67  642.111784.156 738.9111780.065
  764.461776.267 774.8741774.302   786.5 1776.47 795.2731779.195 807.5131780.238
 855.5481779.845 877.0241778.599 896.1111779.729 969.4351781.7811061.3121789.816
1080.7661793.1821091.6411796.8871135.6351819.1421176.1641843.2031206.2241863.286
#Mann= 12 ,-1 , 0
       0      .1       0  37.507    .035       0  42.882     .06       0
 161.427     .05       0 269.241     .06       0 352.699      .1       0
 468.125     .06       0 474.361      .1       0  764.46    .045       0
   786.5      .1       0 855.548     .05       0 896.111      .1       0
#XS Ineff= 2 , 0
          724.89 1782.15  816.67         1781.95
Permanent Ineff=
       F       F
Bank Sta=764.46,786.5
XS Rating Curve= 0 ,0
Exp/Cntr(USF)=0,0
Exp/Cntr=0.3,0.1
LCMann Table=0

Chan Stop Cuts=-1
Use User Specified Reach Order=0
Composite Channel Slope=5